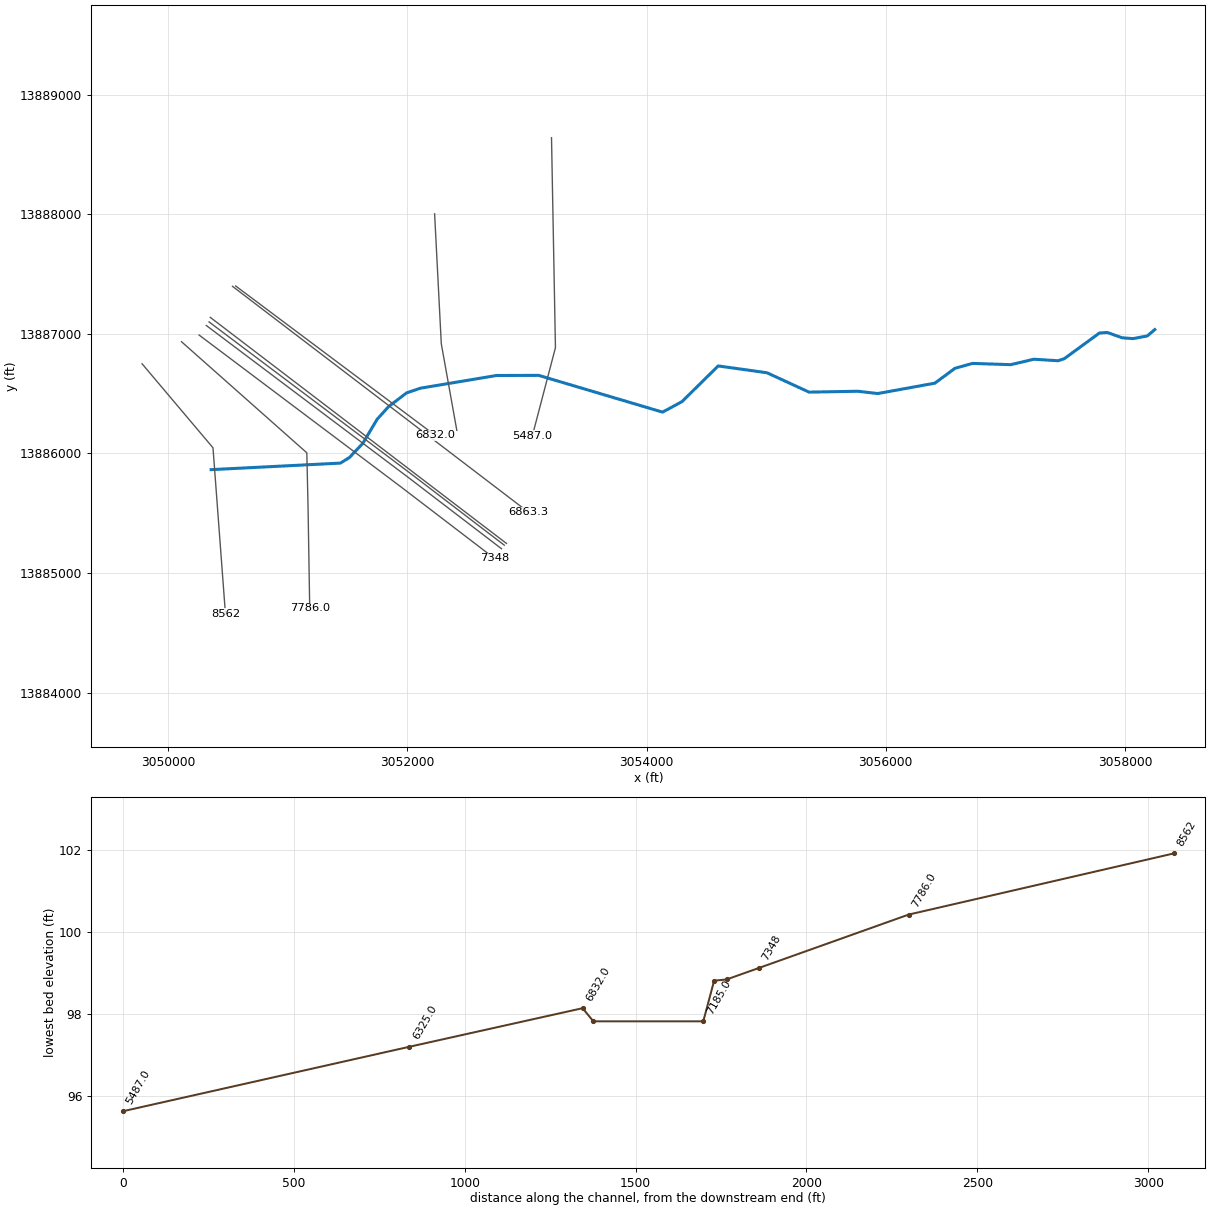
--- E127-00-00.prj (project) ---

Proj Title=E127-00-00
Current Plan=p02
Default Exp/Contr=.3,.1
English Units
Geom File=g01
Flow File=f01
Flow File=f02
Flow File=f04
Plan File=p01
Plan File=p02
Plan File=p04
Y Axis Title=Elevation
X Axis Title(PF)=Main Channel Distance
X Axis Title(XS)=Station
BEGIN DESCRIPTION:
White Oak Bayou Watershed
White Oak Trib. 19.05
HCFCD Unit E127-00-00
Flood Hazard Model
10, 2, 1, 0.2%
Filename E127-00-00
Prepared by:  Mason Liebau  DATE:  March 10, 2004
Reviewed by:  _____________________  DATE:  __________________
STATUS (Final)
END DESCRIPTION:
DSS File=dss
DSS Export Rating Curves= 0
DSS Export Rating Curve Sorted= 0
DSS Export Volume Flow Curves= 0
DXF OffsetX= 0
DXF OffsetY= 0
DXF ScaleX= 1
DXF ScaleY= 10

--- E127-00-00.p02 (plan) ---

Plan Title=Floodway
Version=Version 3.0.1  Mar 2001
Short Identifier=Floodway0607
Geom File=g01
Flow File=f02
Subcritical Flow
K Sum by GR= 0
Std Step Tol= 0.01
Critical Tol= 0.01
Num of Std Step Trials= 20
Max Error Tol= 0.3
Flow Tol Ratio= 0.001
Split Flow NTrial= 30
Split Flow Tol= 0.02
Split Flow Ratio= 0.02
Log Output Level= 0
Friction Slope Method= 1
Unsteady Friction Slope Method= 2
Parabolic Critical Depth
Global Vel Dist= 0 , 0 , 0
Global Log Level= 0
CheckData=True
Encroach Param=-1 ,0,0, 5
Encroach River=E127-00-00
Encroach Reach=Reach - 1
Encroach Node=8562
       1    4942  5060.5       0       0       0       0       0       0
       0       0       0
Encroach Node=7786.0
       1    4942    5042       1    4942    5042       1    4942    5042
       1    4942    5042
Encroach Node=7348
       1 4975.91 5032.32       0       0       0       0       0       0
       0       0       0
Encroach Node=7253.3
       1  4981.1    5081       1  4981.1    5081       1  4981.1    5081
       1  4981.1    5081
Encroach Node=7235.0
       1  4981.1    5081       1  4981.1    5081       1  4981.1    5081
       1  4981.1    5081
Encroach Node=7216.8
       1  4981.1    5081       1  4981.1    5081       1  4981.1    5081
       1  4981.1    5081
Encroach Node=7185.0
       1  4942.9  5057.6       1  4942.9  5057.6       1  4942.9  5057.6
       1  4942.9  5057.6
Encroach Node=7032.0
       1  4942.9  5057.6       1  4942.9  5057.6       1  4942.9  5057.6
       1  4942.9  5057.6
Encroach Node=6863.3
       1  4942.9  5057.6       1  4942.9  5057.6       1  4942.9  5057.6
       1  4942.9  5057.6
Encroach Node=6832.0
       1  4970.5  5029.5       1  4970.5  5029.5       1  4970.5  5029.5
       1  4970.5  5029.5
Encroach Node=6325.0
       1    4965    5024       1    4965    5024       1    4965    5024
       1    4965    5024
Encroach Node=5487.0
       1  4963.8  5042.2       1  4963.8  5042.2       1  4963.8  5042.2
       1  4963.8  5042.2
Encroach Node=5053
       1  4941.6 5038.02       0       0       0       0       0       0
       0       0       0
Encroach Node=4956.5
       1    4937    5032       1    4937    5032       1    4937    5032
       1    4937    5032
Encroach Node=4934.0
       1    4937    5032       1    4937    5032       1    4937    5032
       1    4937    5032
Encroach Node=4911.5
       1    4937    5032       1    4937    5032       1    4937    5032
       1    4937    5032
Encroach Node=4854.0
       1    4942  5037.8       1    4942  5037.8       1    4942  5037.8
       1    4942  5037.8
Encroach Node=4776
       1  4945.6  5035.6       0       0       0       0       0       0
       0       0       0
Encroach Node=4702.0
       1  4955.5  5044.1       1  4955.5  5044.1       1  4955.5  5044.1
       1  4955.5  5044.1
Encroach Node=4676.0
       1  4955.5  5044.1       1  4955.5  5044.1       1  4955.5  5044.1
       1  4955.5  5044.1
Encroach Node=4650.1
       1  4955.5  5044.1       1  4955.5  5044.1       1  4955.5  5044.1
       1  4955.5  5044.1
Encroach Node=4634.0
       1  4962.2  5043.2       1  4962.2  5043.2       1  4962.2  5043.2
       1  4962.2  5043.2
Encroach Node=4095.0
       1  4957.4    5033       1  4957.4    5033       1  4957.4    5033
       1  4957.4    5033
Encroach Node=2854.0
       1  4959.1  5034.1       1  4959.1  5034.1       1  4959.1  5034.1
       1  4959.1  5034.1
Encroach Node=1977.0
       1    4961  5036.2       1    4961  5036.2       1    4961  5036.2
       1    4961  5036.2
Encroach Node=1212
       1 4971.57 5026.87       0       0       0       0       0       0
       0       0       0
Encroach Node=1116.0
       1  4972.9  5025.7       1  4972.9  5025.7       1  4972.9  5025.7
       1  4972.9  5025.7
Encroach Node=1082.0
       1  4972.9  5025.7       1  4972.9  5025.7       1  4972.9  5025.7
       1  4972.9  5025.7
Encroach Node=1048.0
       1  4972.9  5025.7       1  4972.9  5025.7       1  4972.9  5025.7
       1  4972.9  5025.7
Encroach Node=1024.0
       1 4958.25 5041.75       1 4958.25 5041.75       1 4958.25 5041.75
       1 4958.25 5041.75
Encroach Node=731.0
       1  4965.5    5049       1  4965.5    5049       1  4965.5    5049
       1  4965.5    5049
Encroach Reach=E127-00-00_0007
Encroach Node=8562
       1    4942  5060.5       0       0       0       0       0       0
       0       0       0
Encroach Node=7786.0
       1    4942    5042       0       0       0       0       0       0
       0       0       0
Encroach Node=7348
       1 4975.91 5032.32       0       0       0       0       0       0
       0       0       0
Encroach Node=7253.3
       1  4981.1    5081       0       0       0       0       0       0
       0       0       0
Encroach Node=7235.0
       1  4981.1    5081       0       0       0       0       0       0
       0       0       0
Encroach Node=7216.8
       1  4981.1    5081       0       0       0       0       0       0
       0       0       0
Encroach Node=7185.0
       1  4942.9  5057.6       0       0       0       0       0       0
       0       0       0
Encroach Node=7032.0
       1  4942.9  5057.6       0       0       0       0       0       0
       0       0       0
Encroach Node=6863.3
       1  4942.9  5057.6       0       0       0       0       0       0
       0       0       0
Encroach Node=6832.0
       1  4970.5  5029.5       0       0       0       0       0       0
       0       0       0
Encroach Node=6325.0
       1    4965    5024       0       0       0       0       0       0
       0       0       0
Encroach Node=5487.0
       1  4963.8  5042.2       0       0       0       0       0       0
       0       0       0
Encroach Node=5053
       1  4941.6 5038.02       0       0       0       0       0       0
       0       0       0
Encroach Node=4956.5
       1    4937    5032       0       0       0       0       0       0
       0       0       0
Encroach Node=4934.0
       1    4937    5032       0       0       0       0       0       0
       0       0       0
Encroach Node=4911.5
       1    4937    5032       0       0       0       0       0       0
       0       0       0
Encroach Node=4854.0
       1    4942  5037.8       0       0       0       0       0       0
       0       0       0
Encroach Node=4776
       1  4945.6  5035.6       0       0       0       0       0       0
       0       0       0
Encroach Node=4702.0
       1  4955.5  5044.1       0       0       0       0       0       0
       0       0       0
Encroach Node=4676.0
       1  4955.5  5044.1       0       0       0       0       0       0
       0       0       0
Encroach Node=4650.1
       1  4955.5  5044.1       0       0       0       0       0       0
       0       0       0
Encroach Node=4634.0
       1  4962.2  5043.2       0       0       0       0       0       0
       0       0       0
Encroach Node=4095.0
       1  4957.4    5033       0       0       0       0       0       0
       0       0       0
Encroach Node=2854.0
       1  4959.1  5034.1       0       0       0       0       0       0
       0       0       0
Encroach Node=1977.0
       1    4961  5036.2       0       0       0       0       0       0
       0       0       0
Encroach Node=1212
       1 4971.57 5026.87       0       0       0       0       0       0
       0       0       0
Encroach Node=1116.0
       1  4972.9  5025.7       0       0       0       0       0       0
       0       0       0
Encroach Node=1082.0
       1  4972.9  5025.7       0       0       0       0       0       0
       0       0       0
Encroach Node=1048.0
       1  4972.9  5025.7       0       0       0       0       0       0
       0       0       0
Encroach Node=1024.0
       1 4958.25 5041.75       0       0       0       0       0       0
       0       0       0
Encroach Node=731.0
       1  4965.5    5049       0       0       0       0       0       0
       0       0       0
Computation Interval=1HOUR
Output Interval=1HOUR
Run HTab= 0
Run UNet= 0
Run PostProcess= 0
UNET Theta= 1
UNET ZTol= 0.02
UNET ZSATol= 0.1
UNET MxIter= 20
UNET MaxInSteps= 20
UNET DtIC= 0
UNET DtMin= 0
UNET MaxCRTS= 20
UNET WFStab= 2
UNET SFStab= 1
UNET WFX= 1
UNET SFX= 1
UNET Convert EG Bridges=-1
UNET Use Existing IB Tables=-1
Instantaneous Interval=1HOUR
Write IC File= 0
IC Time=0
Write Velocity= 0
Write Detailed= 0

--- E127-00-00.p01 (plan) ---

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Plan Title=FEMA Effective June 2007
Short Identifier=FEMAeff0607
Geom File=g01
Flow File=f01
Encroach Param=-1 ,0,0, 0
DSS File=dss

--- E127-00-00.p04 (plan) ---

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Plan Title=Storage Routing
Program Version=3.13
Short Identifier=Store_Rout
Geom File=g01
Flow File=f04
Unsteady Bridges Friction Slope Method= 1
Encroach Param=-1 ,0,0, 0
UNET Theta Warmup= 1
UNET DSS MLevel= 4
UNET DZMax Abort= 100
UNET Froude Reduction=False
UNET Froude Limit= 1
UNET Froude Power= 10
Echo Input=False
Echo Output=False
Detailed Automatic Start=False, 10

--- E127-00-00.f02 (steady flow) ---

Flow Title=Floodway
Version=Version 3.0.1  Mar 2001
Number of Profiles= 2
Profile Names=1PCT_100yr, 1PCTFloodway_100yrFW
River Rch & RM=E127-00-00,E127-00-00_0007        ,8562
     750     750
River Rch & RM=E127-00-00,E127-00-00_0007        ,7786.0
     910     910
River Rch & RM=E127-00-00,E127-00-00_0007        ,7253.3
     920     920
River Rch & RM=E127-00-00,E127-00-00_0007        ,7185.0
     960     960
River Rch & RM=E127-00-00,E127-00-00_0007        ,6832.0
    1010    1010
River Rch & RM=E127-00-00,E127-00-00_0007        ,6325.0
    1100    1100
River Rch & RM=E127-00-00,E127-00-00_0007        ,5487.0
    1170    1170
River Rch & RM=E127-00-00,E127-00-00_0007        ,4956.5
    1200    1200
River Rch & RM=E127-00-00,E127-00-00_0007        ,4702.0
    1230    1230
River Rch & RM=E127-00-00,E127-00-00_0007        ,4095.0
    1310    1310
River Rch & RM=E127-00-00,E127-00-00_0007        ,2854.0
    1360    1360
River Rch & RM=E127-00-00,E127-00-00_0007        ,1977.0
    1420    1420
River Rch & RM=E127-00-00,E127-00-00_0007        ,1116.0
    1499    1499
Boundary for River Rch & Prof#=E127-00-00,E127-00-00_0007        , 1
Up Type= 0
Dn Type= 3
Dn Slope=.0014
Boundary for River Rch & Prof#=E127-00-00,E127-00-00_0007        , 2
Up Type= 0
Dn Type= 1
Dn Known WS=99.65
DSS Import GetInterval= 0
DSS Import GetPeak= 0
DSS Import FillOption= 0

--- E127-00-00.f01 (steady flow) ---

Flow Title=FEMA Effective June 2007
Version=Version 3.0.1  Mar 2001
Number of Profiles= 4
Profile Names=10PCT_10yr, 2PCT_50yr, 1PCT_100yr, 0.2PCT_500yr
River Rch & RM=E127-00-00,E127-00-00_0007        ,8562
     440     660     750    1110
River Rch & RM=E127-00-00,E127-00-00_0007        ,7786.0
     520     790     910    1370
River Rch & RM=E127-00-00,E127-00-00_0007        ,7253.3
     530     800     920    1400
River Rch & RM=E127-00-00,E127-00-00_0007        ,7185.0
     540     820     960    1430
River Rch & RM=E127-00-00,E127-00-00_0007        ,6832.0
     560     850    1010    1470
River Rch & RM=E127-00-00,E127-00-00_0007        ,6325.0
     600     890    1100    1530
River Rch & RM=E127-00-00,E127-00-00_0007        ,5487.0
     620     920    1170    1580
River Rch & RM=E127-00-00,E127-00-00_0007        ,4956.5
     630     940    1200    1600
River Rch & RM=E127-00-00,E127-00-00_0007        ,4702.0
     660     980    1230    1660
River Rch & RM=E127-00-00,E127-00-00_0007        ,4095.0
     710    1060    1310    1790
River Rch & RM=E127-00-00,E127-00-00_0007        ,2854.0
     760    1130    1360    1880
River Rch & RM=E127-00-00,E127-00-00_0007        ,1977.0
     800    1190    1420    1980
River Rch & RM=E127-00-00,E127-00-00_0007        ,1116.0
     862    1284    1499    2121
Boundary for River Rch & Prof#=E127-00-00,E127-00-00_0007        , 1
Up Type= 0
Dn Type= 3
Dn Slope=.0014
Boundary for River Rch & Prof#=E127-00-00,E127-00-00_0007        , 2
Up Type= 0
Dn Type= 3
Dn Slope=.0014
Boundary for River Rch & Prof#=E127-00-00,E127-00-00_0007        , 3
Up Type= 0
Dn Type= 3
Dn Slope=.0014
Boundary for River Rch & Prof#=E127-00-00,E127-00-00_0007        , 4
Up Type= 0
Dn Type= 3
Dn Slope=.0014
DSS Import GetInterval= 0
DSS Import GetPeak= 0
DSS Import FillOption= 0

--- E127-00-00.f04 (steady flow) ---

Flow Title= Storage Routing
Version=Version 3.0.1  Mar 2001
Number of Profiles= 7
Profile Names=.25x10% flood,.50x10% flood,10% flood,2% flood,1% flood,0.2% flood,1.25x0.2% flood
River Rch & RM=E127-00-00,E127-00-00_0007        ,8562
      93     185     370     510     580     810    1013
River Rch & RM=E127-00-00,E127-00-00_0007        ,7786
     103     205     410     570     650     910    1138
River Rch & RM=E127-00-00,E127-00-00_0007        ,7253.25
     108     215     430     600     680     950    1188
River Rch & RM=E127-00-00,E127-00-00_0007        ,6876.8
     120     240     480     670     760    1070    1338
River Rch & RM=E127-00-00,E127-00-00_0007        ,6325
     135     270     540     750     850    1190    1488
River Rch & RM=E127-00-00,E127-00-00_0007        ,4911.5
     145     290     580     800     910    1270    1588
River Rch & RM=E127-00-00,E127-00-00_0007        ,4702.0
     173     345     690     960    1100    1590    1988
Boundary for River Rch & Prof#=E127-00-00,E127-00-00_0007        , 1
Up Type= 0
Dn Type= 3
Dn Slope=.0014
Boundary for River Rch & Prof#=E127-00-00,E127-00-00_0007        , 2
Up Type= 0
Dn Type= 3
Dn Slope=.0014
Boundary for River Rch & Prof#=E127-00-00,E127-00-00_0007        , 3
Up Type= 0
Dn Type= 3
Dn Slope=.0014
Boundary for River Rch & Prof#=E127-00-00,E127-00-00_0007        , 4
Up Type= 0
Dn Type= 3
Dn Slope=.0014
Boundary for River Rch & Prof#=E127-00-00,E127-00-00_0007        , 5
Up Type= 0
Dn Type= 3
Dn Slope=.0014
Boundary for River Rch & Prof#=E127-00-00,E127-00-00_0007        , 6
Up Type= 0
Dn Type= 3
Dn Slope=.0014
Boundary for River Rch & Prof#=E127-00-00,E127-00-00_0007        , 7
Up Type= 0
Dn Type= 3
Dn Slope=.0014
DSS Import GetInterval= 0
DSS Import GetPeak= 0
DSS Import FillOption= 0

--- E127-00-00.g01 (geometry) ---

Geom Title=E127-00-00 June 2007
Version=Version 3.0.1  Mar 2001

River Reach=E127-00-00      ,E127-00-00_0007
Reach XY= 30
      3050359.66     13885863.79      3051440.38     13885918.48
      3051515.91     13885965.36      3051628.25       13886084.
      3051748.54     13886286.54      3051843.16      13886390.7
      3051993.34     13886505.29      3052107.92     13886544.35
      3052745.07     13886651.12      3053098.37     13886651.99
      3054133.96      13886344.7      3054296.29     13886432.37
      3054599.24     13886730.98      3055007.22     13886673.69
      3055358.75       13886512.      3055766.77     13886519.18
      3055934.31     13886500.08      3056410.87     13886586.89
      3056578.84      13886711.2      3056725.54       13886752.
      3057045.85     13886741.58      3057238.25       13886787.
      3057440.78      13886774.4      3057491.99     13886790.89
      3057786.74     13887006.16      3057852.71      13887010.5
      3057976.84     13886966.23      3058067.12     13886959.28
      3058186.61     13886981.47      3058249.41      13887034.8

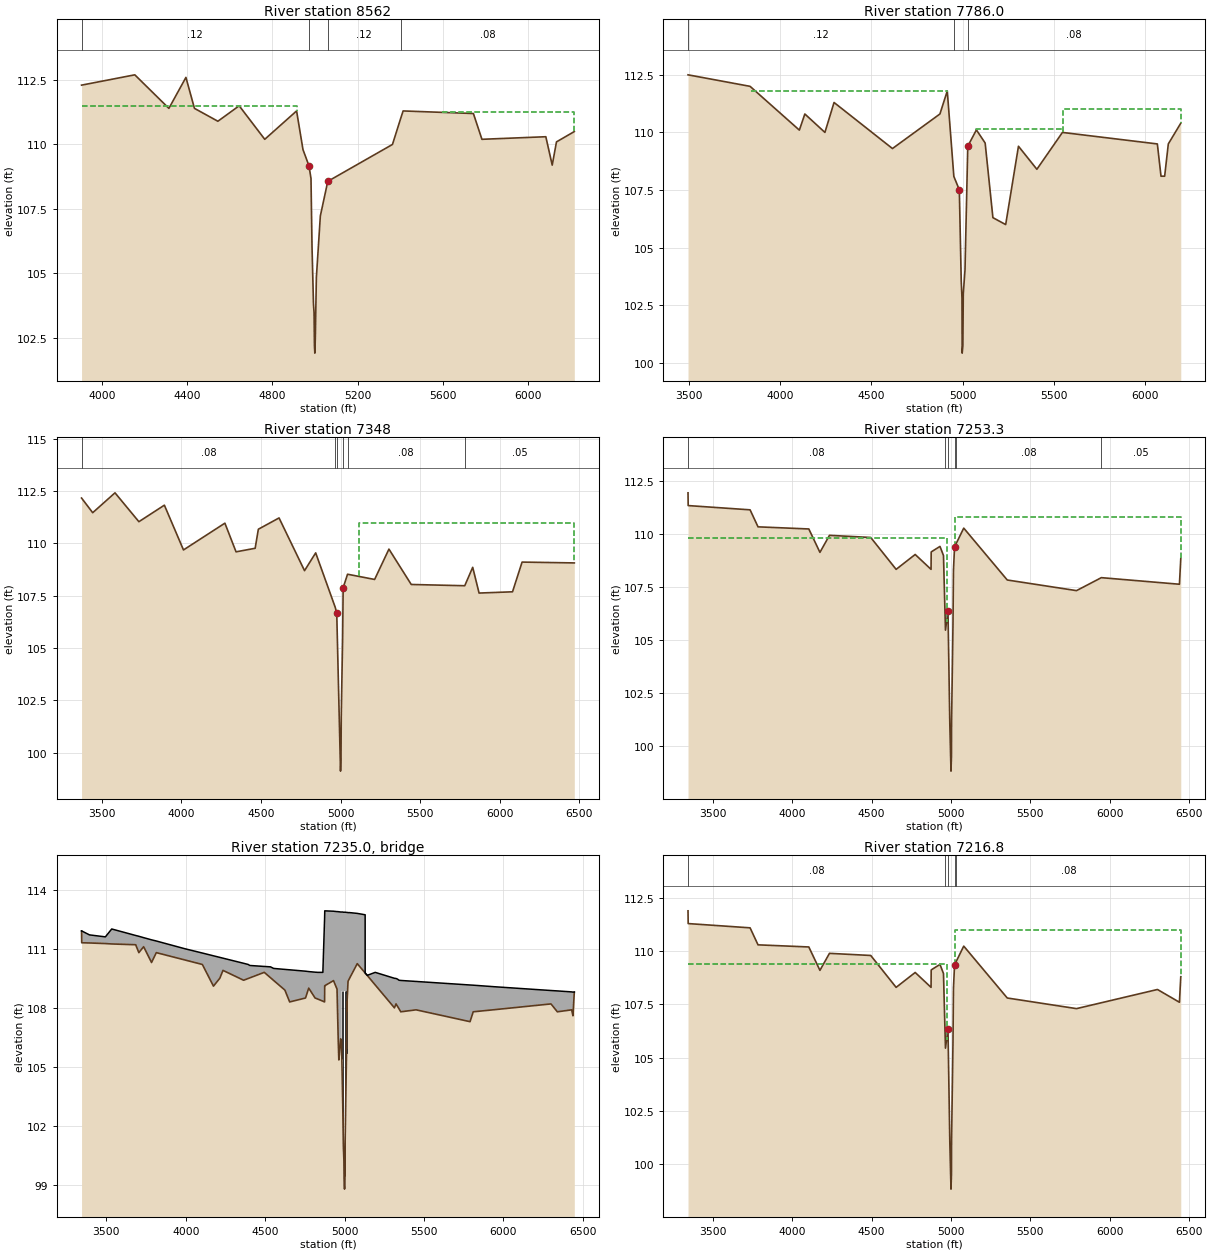
Type RM Length L Ch R = 1 ,8562    ,673.4,776,667.5
BEGIN DESCRIPTION:
Cross Section XS08
Located At: 2ND US SOUTHERN PACIFIC RR
***Ineffective area in the right and left overbanks indicates ponding water***
***100-year and 500-year storms are not contained on right overbank.  Ground eleveations continure to decrease with increaseing distance from the channel.  Water flows toward the E117 (Cole Creek) watershed.  The area between the E127 and E117 watersheds has not been studied.***
END DESCRIPTION:
XS GIS Cut Line= 3
      3049781.99      13886749.1      3050375.09      13886046.5
      3050479.34      13884656.6
#Sta/Elev= 30
  3904.6   112.3  4154.6   112.7  4314.6   111.4  4394.6   112.6  4434.6   111.4
  4544.6   110.9  4644.6   111.5  4764.6   110.2  4914.1   111.3  4944.1   109.8
  4972.3  109.17  4981.7  108.68  4986.5  106.03  4993.3  103.83  4996.1  103.47
  4997.9  102.19  4999.7  101.91  5001.9  102.46  5006.9  104.84  5025.6  107.23
  5060.5  108.57  5364.1     110  5402.4     111  5414.1   111.3  5744.1   111.2
  5784.1   110.2  6084.1   110.3  6114.1   109.2  6134.1   110.1  6217.8   110.5
#Mann= 4 ,-1 , 0
  3904.6     .12       0  4972.3     .08       0  5060.5     .12       0
  5402.4     .08       0
#XS Ineff= 2 , 0
       0 4914.13   111.5 5596.68       0  111.25
Permanent Ineff=
       F       F
Bank Sta=4972.3,5060.5
XS Rating Curve= 0
Exp/Cntr=.3,.1

Type RM Length L Ch R = 1 ,7786.0  ,390.4,438,477.6
BEGIN DESCRIPTION:
Cross Section XS07
Located At: US SOUTHERN PACIFIC RR
***Ineffective area in the right and left overbanks indicates ponding water***
***100-year and 500-year storms are not contained on right overbank.  Ground eleveations continure to decrease with increaseing distance from the channel.  Water flows toward the E117 (Cole Creek) watershed.  The area between the E127 and E117 watersheds has not been studied.***
END DESCRIPTION:
XS GIS Cut Line= 4
      3050111.75     13886933.48      3051159.58     13886004.62
      3051169.82     13885553.79       3051183.8     13884705.62
#Sta/Elev= 30
  3495.6   112.5  3835.6     112  4105.6   110.1  4135.6   110.8  4245.6     110
  4295.6   111.3  4615.6   109.3  4875.6   110.8  4915.9   111.8  4951.9  108.09
  4981.9  107.51  4992.4  103.54  4996.4  102.82  4997.5  100.42  5001.3  100.74
  5003.6  102.99    5013  104.03  5028.2   109.4  5075.5  110.11  5123.4  109.54
  5165.9   106.3  5235.9     106  5305.9   109.4  5406.8   108.4  5546.8     110
  6066.8   109.5  6086.8   108.1  6106.8   108.1  6126.8   109.5  6195.1   110.4
#Mann= 3 ,-1 , 0
  3495.6     .12       0  4951.9     .08       0  5028.2     .08       0
#XS Ineff= 3 ,-1
    3843 4916.36  111.79 5075.37 5547.64  110.13 5547.65  6194.6     111
Permanent Ineff=
       F       F       F
Bank Sta=4981.9,5028.2
XS Rating Curve= 0
Exp/Cntr=.3,.1

Type RM Length L Ch R = 1 ,7348    ,94.5,94.7,100.8
BEGIN DESCRIPTION:
SOUTHERN PACIFIC - 4
Interpolated channel, LIDAR overbanks
END DESCRIPTION:
XS GIS Cut Line= 3
      3050258.67      13886989.4      3051941.59     13885723.46
      3052726.34     13885123.36
#Sta/Elev= 30
  3373.7  112.17  3443.7  111.47  3583.7  112.42  3733.7  111.04  3893.7  111.83
  4013.7  109.69  4273.7  110.97  4343.7   109.6  4463.7  109.77  4483.7  110.68
  4613.7  111.22  4773.7   108.7  4843.7  109.55 4965.91  106.96 4975.91  106.68
 4999.64   99.12 5002.58   99.69 5004.37  101.81 5012.98  105.53 5016.18  107.88
  5043.7  108.53  5213.7  108.28  5303.7  109.73  5443.7  108.04  5779.6  107.98
  5829.6  108.86  5869.6  107.63  6079.6  107.69  6139.6  109.11  6467.5  109.07
#Mann= 6 ,-1 , 0
  3373.7     .08       0 4965.91     .05       0 4975.91     .05       0
 5016.18     .05       0  5043.7     .08       0  5779.6     .05       0
#XS Ineff= 2 , 0
       0  4613.7  111.22 5116.18       0     111
Permanent Ineff=
       F       F
Bank Sta=4975.91,5016.18
XS Rating Curve= 0
Exp/Cntr=.5,.3

Type RM Length L Ch R = 1 ,7253.3  ,36,36.5,38.3
BEGIN DESCRIPTION:
SOUTHERN PACIFIC - 3
E127-00-00-04
***The Levee option was used on this cross-section does not describe a certified levee system but because after reviewing the mapping it was determined that water under that elevation could not back up into the lower-lying areas in the right overbank.***
END DESCRIPTION:
XS GIS Cut Line= 3
      3050318.78     13887069.36      3052002.02     13885803.14
      3052787.09      13885202.8
#Sta/Elev= 30
  3343.5  111.93  3344.5  111.33  3734.5  111.13  3784.5  110.33  4104.5  110.23
  4174.5  109.13  4234.5  109.93  4494.5  109.83  4654.5  108.33  4774.5  109.03
  4874.5  108.33  4875.3  109.15  4930.7  109.41  4952.8  108.98  4965.3  105.47
  4981.1  106.37  4992.8  101.02  5000.1   98.84    5003   99.53  5003.6  101.08
  5012.6  105.72  5015.6  108.27  5022.4  109.38  5031.9  109.53  5080.4  110.27
  5354.5  107.83  5790.8  107.33  5947.3  107.94  6439.1  107.63  6447.6  108.83
#Mann= 6 ,-1 , 0
  3343.5     .08       0  4965.3     .05       0  4981.1     .05       0
  5022.4     .05       0  5031.9     .08       0  5947.3     .05       0
#XS Ineff= 2 , 0
       0    4972   109.8    5024       0   110.8
Permanent Ineff=
       F       F
Bank Sta=4981.1,5022.4
XS Rating Curve= 0
Exp/Cntr=.5,.3

Type RM Length L Ch R = 3 ,7235.0  ,,,
BEGIN DESCRIPTION:
SOUTHERN PACIFIC
Structure ID: E127-00-00-04
END DESCRIPTION:
Bridge Culvert--1,0,-1,-1, 0
Deck Dist Width WeirC Skew NumUp NumDn MinLoCord MaxHiCord MaxSubmerge Is_Ogee
10,16.5,2.6,0, 82, 82, , , .95, 0, ,,,
  3343.5  3344.5  3393.5  3493.5  3533.5  3684.5  3704.5  3734.5  3784.5  3814.5
  3993.5  4104.5  4174.5  4214.5  4234.5  4364.5  4393.5  4403.5  4494.5  4533.5
  4553.5  4624.5  4654.5  4754.5  4774.5  4814.5  4833.5  4863.5  4874.5  4875.3
  4875.5  4930.4  4930.7  4952.8  4954.4  4960.1  4964.2  4965.3  4968.3  4975.8
  4981.1    4982 4982.11  4982.2  4983.3    4989  4992.8  4996.2  4997.5  4998.5
  5000.1  5001.4  5002.4    5003  5003.6  5012.6  5012.8 5013.69  5013.8  5015.6
  5022.4  5031.9  5080.3  5080.4    5130  5130.1  5143.5  5193.5  5314.5  5324.5
  5333.5  5343.5  5354.5  5450.8  5790.8  5810.8  5947.3  6300.8  6340.8  6430.8
  6439.1  6447.6
   111.9   111.9   111.7   111.6     112  111.67  111.63  111.56  111.45  111.39
     111  110.78  110.64  110.56  110.52  110.26   110.2  110.15   110.1  110.08
     110  109.95  109.93  109.86  109.84  109.81   109.8   109.8  112.54  112.84
  112.92   112.9   112.9  112.88  112.88  112.88  112.87  112.87  112.87  112.86
  112.86  112.86  112.86  112.86  112.86  112.86  112.85  112.85  112.85  112.85
  112.85  112.85  112.85  112.85  112.85  112.84  112.84  112.84  112.84  112.84
  112.83  112.83  112.79  112.79  112.72  109.77  109.65   109.8   109.5  109.49
  109.46   109.4  109.39  109.34  109.16  109.15  109.07  108.88  108.86  108.81
   108.8   108.8
                                                                                
                                                                                
                                                                                
                                                                                
          105.97  105.92  108.86  108.86  108.86  108.85  108.85  108.85  108.85
  108.85  108.85  108.85  108.85  108.85  108.84  108.84  108.84
                                                                                
                                                                                
                
  3343.5  3344.5  3393.5  3493.5  3533.5  3684.5  3704.5  3734.5  3784.5  3814.5
  3993.5  4104.5  4174.5  4214.5  4234.5  4364.5  4393.5  4403.5  4494.5  4533.5
  4553.5  4624.5  4654.5  4754.5  4774.5  4814.5  4833.5  4863.5  4874.5  4875.3
  4875.5  4930.4  4930.7  4952.8  4954.4  4960.1  4964.2  4965.3  4968.3  4975.8
  4981.1    4982 4982.11  4982.2  4983.3    4989  4992.8  4996.2  4997.5  4998.5
  5000.1  5001.4  5002.4    5003  5003.6  5012.6  5012.8 5013.69  5013.8  5015.6
  5022.4  5031.9  5080.3  5080.4    5130  5130.1  5143.5  5193.5  5314.5  5324.5
  5333.5  5343.5  5354.5  5450.8  5790.8  5810.8  5947.3  6300.8  6340.8  6430.8
  6439.1  6447.6
   111.9   111.9   111.7   111.6     112  111.67  111.63  111.56  111.45  111.39
     111  110.78  110.64  110.56  110.52  110.26   110.2  110.15   110.1  110.08
     110  109.95  109.93  109.86  109.84  109.81   109.8   109.8  112.54  112.84
  112.92   112.9   112.9  112.88  112.88  112.88  112.87  112.87  112.87  112.86
  112.86  112.86  112.86  112.86  112.86  112.86  112.85  112.85  112.85  112.85
  112.85  112.85  112.85  112.85  112.85  112.84  112.84  112.84  112.84  112.84
  112.83  112.83  112.79  112.79  112.72  109.77  109.65   109.8   109.5  109.49
  109.46   109.4  109.39  109.34  109.16  109.15  109.07  108.88  108.86  108.81
   108.8   108.8
                                                                                
                                                                                
                                                                                
                                                                                
          105.97  105.92  108.86  108.86  108.86  108.85  108.85  108.85  108.85
  108.85  108.85  108.85  108.85  108.85  108.84  108.84  108.84
                                                                                
                                                                                
                
Pier Skew, UpSta & Num, DnSta & Num=  ,4983.3, 2 ,4983.3, 2 , 0 , 0 , 0 ,,
       1       1
  104.22  109.86
       1       1
  104.55  110.19
Pier Skew, UpSta & Num, DnSta & Num=  ,4992.8, 2 ,4992.8, 2 , 0 , 0 , 0 ,,
     1.2     1.2
   99.86  109.85
     1.2     1.2
  100.19  110.18
Pier Skew, UpSta & Num, DnSta & Num=  ,5003, 2 ,5003, 2 , 0 , 0 , 0 ,,
     1.2     1.2
   98.23  109.85
     1.2     1.2
   98.56  110.18
Pier Skew, UpSta & Num, DnSta & Num=  ,5012.6, 2 ,5012.6, 2 , 0 , 0 , 0 ,,
       1       1
  104.43  109.84
       1       1
  104.76  110.17
BR Coef= 1 , 1 , 1 ,.95, 0 ,,,.8,0,1.33,0,
WSPro=,,,, 1 ,,,, 0 ,,,, 0 ,,,,-1 ,-1 ,-1 , 0 , 0 , 0 , 0 , 0
BR U #Sta/Elev= 82
  3343.5   111.9  3344.5   111.3  3393.5  111.29  3493.5  111.26  3533.5  111.24
  3684.5   111.2  3704.5   110.8  3734.5   111.1  3784.5   110.3  3814.5   110.8
  3993.5  110.43  4104.5   110.2  4174.5   109.1  4214.5   109.5  4234.5   109.9
  4364.5   109.4  4393.5  109.49  4403.5  109.52  4494.5   109.8  4533.5  109.53
  4553.5  109.39  4624.5   108.9  4654.5   108.3  4754.5   108.5  4774.5     109
  4814.5   108.5  4833.5  108.44  4863.5  108.34  4874.5   108.3  4875.3  109.12
  4875.5  109.12  4930.4  109.38  4930.7  109.38  4952.8  108.95  4954.4   108.4
  4960.1  106.47  4964.2  105.36  4965.3  105.44  4968.3  105.67  4975.8  106.43
  4981.1  106.34    4982  105.97 4982.11  105.92  4982.2  105.89  4983.3  105.43
    4989  103.04  4992.8  100.99  4996.2  100.28  4997.5   99.27  4998.5   98.96
  5000.1   98.81  5001.4   98.89  5002.4   99.23    5003    99.5  5003.6  101.05
  5012.6  105.69  5012.8  105.86 5013.69  106.62  5013.8  106.71  5015.6  108.24
  5022.4  109.35  5031.9   109.5  5080.3  110.24  5080.4  110.24    5130  109.77
  5130.1  109.76  5143.5  109.64  5193.5  109.16  5314.5     108  5324.5   108.2
  5333.5  108.08  5343.5  107.95  5354.5   107.8  5450.8   107.9  5790.8   107.3
  5810.8   107.8  5947.3  107.91  6300.8   108.2  6340.8   107.8  6430.8   107.9
  6439.1   107.6  6447.6   108.8
BR U #Mann= 5
  3343.5     .08  4965.3     .05  4981.1     .05  5022.4     .05  5031.9     .08
BR U Banks=4981.1,5022.4
BR D #Sta/Elev= 82
  3343.5   111.9  3344.5   111.3  3393.5  111.29  3493.5  111.26  3533.5  111.24
  3684.5   111.2  3704.5   110.8  3734.5   111.1  3784.5   110.3  3814.5   110.8
  3993.5  110.43  4104.5   110.2  4174.5   109.1  4214.5   109.5  4234.5   109.9
  4364.5   109.4  4393.5  109.49  4403.5  109.52  4494.5   109.8  4533.5  109.53
  4553.5  109.39  4624.5   108.9  4654.5   108.3  4754.5   108.5  4774.5     109
  4814.5   108.5  4833.5  108.44  4863.5  108.34  4874.5   108.3  4875.3  109.12
  4875.5  109.12  4930.4  109.38  4930.7  109.38  4952.8  108.95  4954.4   108.4
  4960.1  106.47  4964.2  105.36  4965.3  105.44  4968.3  105.67  4975.8  106.43
  4981.1  106.34    4982  105.97 4982.11  105.92  4982.2  105.89  4983.3  105.43
    4989  103.04  4992.8  100.99  4996.2  100.28  4997.5   99.27  4998.5   98.96
  5000.1   98.81  5001.4   98.89  5002.4   99.23    5003    99.5  5003.6  101.05
  5012.6  105.69  5012.8  105.86 5013.69  106.62  5013.8  106.71  5015.6  108.24
  5022.4  109.35  5031.9   109.5  5080.3  110.24  5080.4  110.24    5130  109.77
  5130.1  109.76  5143.5  109.64  5193.5  109.16  5314.5     108  5324.5   108.2
  5333.5  108.08  5343.5  107.95  5354.5   107.8  5450.8   107.9  5790.8   107.3
  5810.8   107.8  5947.3  107.91  6300.8   108.2  6340.8   107.8  6430.8   107.9
  6439.1   107.6  6447.6   108.8
BR D #Mann= 5
  3343.5     .08  4965.3     .05  4981.1     .05  5022.4     .05  5031.9     .08
BR D Banks=4981.1,5022.4
BC Design=,, 0 ,, 0 ,,,,,,

Type RM Length L Ch R = 1 ,7216.8  ,25.6,31.8,25
BEGIN DESCRIPTION:
SOUTHERN PACIFIC - 2
E127-00-00-04
END DESCRIPTION:
XS GIS Cut Line= 3
      3050342.28      13887098.9      3052025.46     13885832.72
      3052810.46     13885232.43
#Sta/Elev= 30
  3343.5   111.9  3344.5   111.3  3734.5   111.1  3784.5   110.3  4104.5   110.2
  4174.5   109.1  4234.5   109.9  4494.5   109.8  4654.5   108.3  4774.5     109
  4874.5   108.3  4875.3  109.12  4930.7  109.38  4952.8  108.95  4965.3  105.44
  4981.1  106.34  4992.8  100.99  5000.1   98.81    5003    99.5  5003.6  101.05
  5012.6  105.69  5015.6  108.24  5022.4  109.35  5031.9   109.5  5080.4  110.24
  5354.5   107.8  5790.8   107.3  6300.8   108.2  6439.1   107.6  6447.6   108.8
#Mann= 5 ,-1 , 0
  3343.5     .08       0  4965.3     .05       0  4981.1     .05       0
  5022.4     .05       0  5031.9     .08       0
#XS Ineff= 2 , 0
       0  4972.1  109.38  5023.8       0     111
Permanent Ineff=
       F       F
Bank Sta=4981.1,5022.4
XS Rating Curve= 0
Exp/Cntr=.5,.3

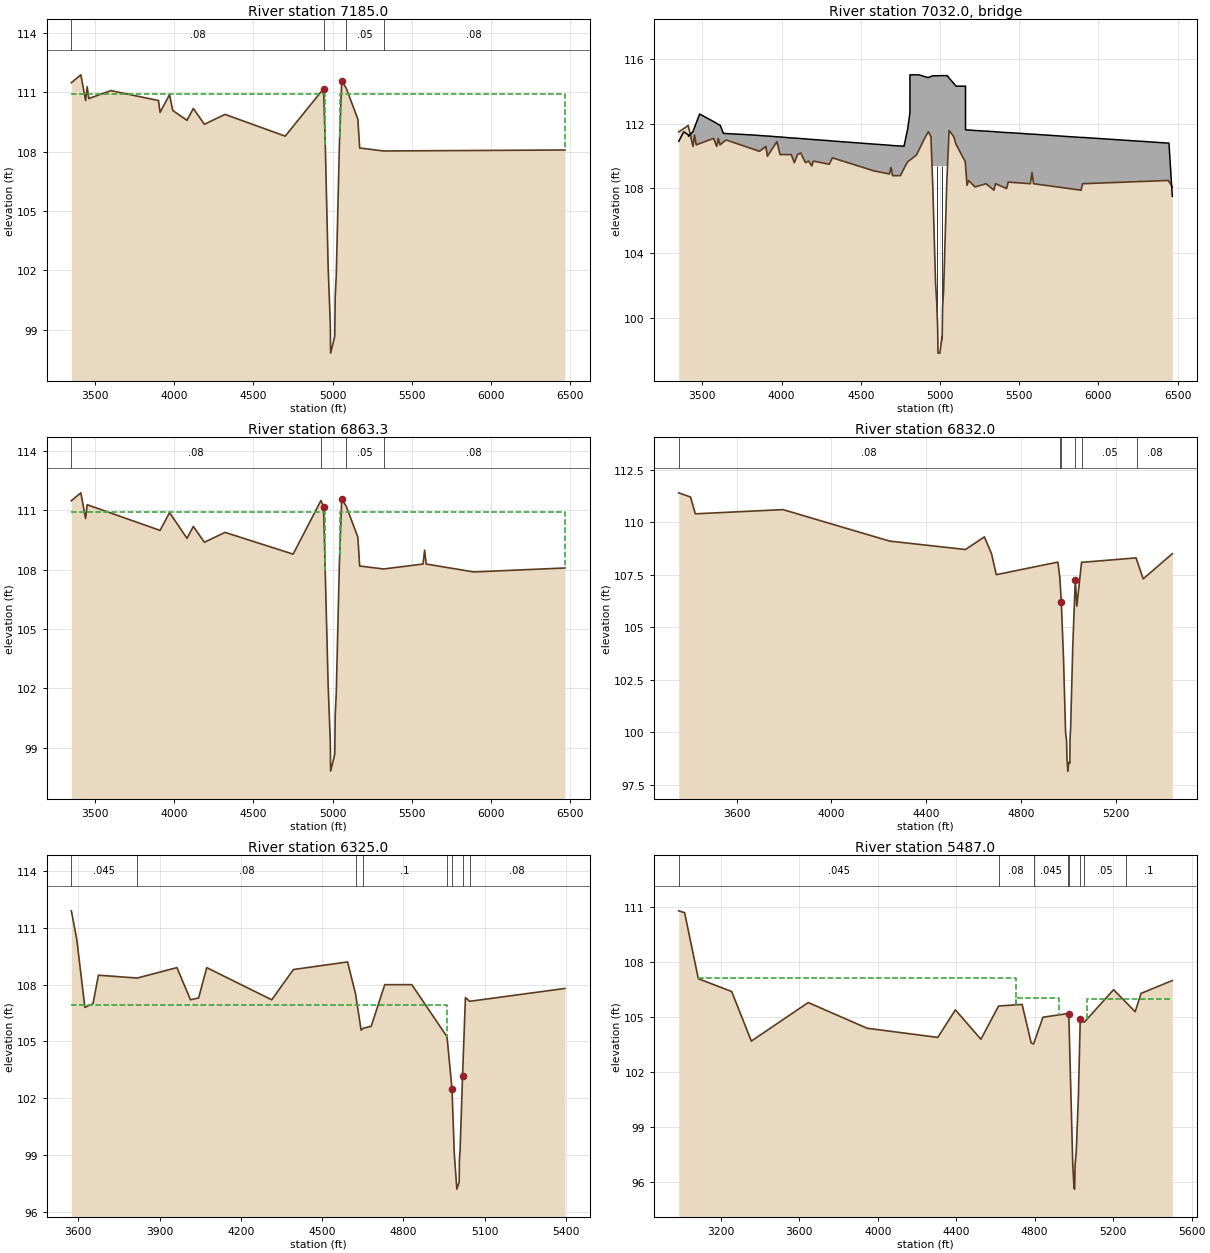
Type RM Length L Ch R = 1 ,7185.0  ,320.4,321.7,319.4
BEGIN DESCRIPTION:
US 290 - 3
E127-00-00-03
END DESCRIPTION:
XS GIS Cut Line= 2
      3050352.14     13887137.17      3052828.86     13885246.84
#Sta/Elev= 30
  3350.8  111.49  3410.8  111.89  3440.8  110.59  3450.8  111.29  3460.8  110.69
  3600.8  111.09  3900.8  110.59  3910.8  109.99  3970.8  110.89  3990.8  110.09
  4080.8  109.59  4120.8  110.19  4190.8  109.39  4320.8  109.89  4700.8  108.79
  4942.9  111.19  4954.3   108.2    4972  102.14  4985.5    99.3  4987.4   97.82
  5013.6   98.67  5016.4  100.63    5023  101.74    5043   108.4  5057.6  111.58
  5086.7   111.2  5159.4  109.65  5170.8  108.19    5322  108.04  6466.5  108.09
#Mann= 4 ,-1 , 0
  3350.8     .08       0  4942.9     .04       0  5086.7     .05       0
    5322     .08       0
#XS Ineff= 2 , 0
       0  4953.9   110.9  5044.5       0   110.9
Permanent Ineff=
       F       F
Bank Sta=4942.9,5057.6
XS Rating Curve= 0
Exp/Cntr=.5,.3

Type RM Length L Ch R = 3 ,7032.0  ,,,
BEGIN DESCRIPTION:
US 290
Structure ID: E127-00-00-03
END DESCRIPTION:
Bridge Culvert--1,0,-1,-1, 0
Deck Dist Width WeirC Skew NumUp NumDn MinLoCord MaxHiCord MaxSubmerge Is_Ogee
10,290.4,3,0, 94, 94, , , .95, 0, ,,,
  3350.8  3382.8  3410.8  3412.8  3440.8  3450.8  3460.8  3482.8  3570.8  3590.8
  3600.8  3610.8  3612.8  3632.8  3650.8  3822.8  3860.8  3900.8  3910.8  3970.8
  3990.8  4060.8  4080.8  4100.8  4120.8  4150.8  4170.8  4190.8  4200.8  4300.8
  4320.8  4580.8  4680.8  4690.8  4700.8  4750.8  4770.8  4772.8  4795.7 4810.09
  4810.2 4810.31  4810.4  4851.1  4865.3  4908.7  4926.4  4942.9  4953.8 4953.91
    4954  4954.3    4972  4979.1  4983.6  4985.5  4987.4  4999.3    5013  5013.6
  5014.5  5016.4    5023    5043  5044.7 5044.79  5044.9  5053.9  5057.6  5086.7
  5100.6  5101.7  5159.4    5161 5161.09  5161.2 5161.31  5170.8  5180.8  5220.8
  5290.8    5322  5340.8  5350.8  5420.8  5430.8  5570.8  5580.8  5590.8  5890.8
  5900.8  6440.8  6445.4  6466.5
  110.91   111.5  111.31  111.22  111.52  111.78  112.03   112.6  112.13  112.02
  111.96  111.91   111.9   111.4  111.39   111.3  111.27  111.24  111.24  111.19
  111.18  111.12  111.11   111.1  111.08  111.06  111.04  111.03  111.02  110.95
  110.93  110.74  110.67  110.66  110.65  110.62   110.6   110.6  111.66  112.66
  115.02  115.02  115.02  115.02  115.02   114.9  114.85  114.92  114.96  114.96
  114.96  114.96  114.96  114.96  114.96  114.96  114.96  114.97  114.97  114.97
  114.97  114.97  114.97  114.97  114.97  114.97  114.97  114.87  114.82  114.49
  114.33  114.32  114.32  114.32  114.32  114.32  111.62  111.61  111.61  111.58
  111.54  111.52  111.51   111.5  111.45  111.45  111.36  111.35  111.35  111.15
  111.15   110.8   110.8  107.51
                                                                                
                                                                                
                                                                                
                                                                                
                                                                          108.31
  109.37  109.37  109.37  109.37  109.37  109.37  109.37  109.38  109.38  109.38
  109.38  109.38  109.38  109.38  109.38  109.38  108.86
                                                                                
                                                                                
                                
  3350.8  3382.8  3410.8  3412.8  3440.8  3450.8  3460.8  3482.8  3570.8  3590.8
  3600.8  3610.8  3612.8  3632.8  3650.8  3822.8  3860.8  3900.8  3910.8  3970.8
  3990.8  4060.8  4080.8  4100.8  4120.8  4150.8  4170.8  4190.8  4200.8  4300.8
  4320.8  4580.8  4680.8  4690.8  4700.8  4750.8  4770.8  4772.8  4795.7 4810.09
  4810.2 4810.31  4810.4  4851.1  4865.3  4908.7  4926.4  4942.9  4953.8 4953.91
    4954  4954.3    4972  4979.1  4983.6  4985.5  4987.4  4999.3    5013  5013.6
  5014.5  5016.4    5023    5043  5044.7 5044.79  5044.9  5053.9  5057.6  5086.7
  5100.6  5101.7  5159.4    5161 5161.09  5161.2 5161.31  5170.8  5180.8  5220.8
  5290.8    5322  5340.8  5350.8  5420.8  5430.8  5570.8  5580.8  5590.8  5890.8
  5900.8  6440.8  6445.4  6466.5
  110.91   111.5  111.31  111.22  111.52  111.78  112.03   112.6  112.13  112.02
  111.96  111.91   111.9   111.4  111.39   111.3  111.27  111.24  111.24  111.19
  111.18  111.12  111.11   111.1  111.08  111.06  111.04  111.03  111.02  110.95
  110.93  110.74  110.67  110.66  110.65  110.62   110.6   110.6  111.66  112.66
  115.02  115.02  115.02  115.02  115.02   114.9  114.85  114.92  114.96  114.96
  114.96  114.96  114.96  114.96  114.96  114.96  114.96  114.97  114.97  114.97
  114.97  114.97  114.97  114.97  114.97  114.97  114.97  114.87  114.82  114.49
  114.33  114.32  114.32  114.32  114.32  114.32  111.62  111.61  111.61  111.58
  111.54  111.52  111.51   111.5  111.45  111.45  111.36  111.35  111.35  111.15
  111.15   110.8   110.8  107.51
                                                                                
                                                                                
                                                                                
                                                                                
                                                                          108.31
  109.37  109.37  109.37  109.37  109.37  109.37  109.37  109.38  109.38  109.38
  109.38  109.38  109.38  109.38  109.38  109.38  108.86
                                                                                
                                                                                
                                
Pier Skew, UpSta & Num, DnSta & Num=  ,4983.6, 2 ,4983.6, 2 , 0 , 0 , 0 ,,
     1.3     1.3
   98.69  110.37
     1.3     1.3
  100.61  112.29
Pier Skew, UpSta & Num, DnSta & Num=  ,5013.6, 2 ,5013.6, 2 , 0 , 0 , 0 ,,
     1.3     1.3
   97.84  110.38
     1.3     1.3
   99.76   112.3
BR Coef= 1 , 1 , 1 ,1.25, 0 ,,,.8,0,2,0,
WSPro=,,,, 1 ,,,, 0 ,,,, 0 ,,,,-1 ,-1 ,-1 , 0 , 0 , 0 , 0 , 0
BR U #Sta/Elev= 79
  3350.8  111.49  3382.8   111.7  3410.8  111.89  3412.8   111.8  3440.8  110.59
  3450.8  111.29  3460.8  110.69  3482.8  110.77  3570.8  111.09  3590.8  110.59
  3600.8  111.09  3610.8  110.69  3612.8   110.7  3632.8  110.86  3650.8  110.99
  3822.8  110.42  3860.8  110.29  3900.8  110.59  3910.8  109.99  3970.8  110.89
  3990.8  110.09  4060.8  110.09  4080.8  109.59  4100.8  110.09  4120.8  110.19
  4150.8  109.59  4170.8  109.69  4190.8  109.39  4200.8  109.69  4300.8  109.49
  4320.8  109.89  4580.8  109.09  4680.8  108.89  4690.8  109.29  4700.8  108.79
  4750.8  108.79  4770.8  109.19  4772.8  109.23  4795.7  109.64  4851.1  110.06
  4865.3  110.34  4908.7   111.2  4926.4   111.5  4942.9  111.19  4954.3   108.2
    4972  102.14  4979.1  101.04  4983.6   99.87  4985.5    99.3  4987.4   97.82
  4999.3   97.82    5013   98.84  5013.6   98.67  5014.5   99.25  5016.4  100.63
    5023  101.74    5043   108.4  5057.6  111.58  5086.7   111.2  5100.6  110.74
  5101.7  110.72  5159.4  109.65  5170.8  108.19  5180.8  108.49  5220.8  108.09
  5290.8  108.29    5322  108.04  5340.8  107.89  5350.8  108.29  5420.8  107.99
  5430.8  108.39  5570.8  108.29  5580.8  108.99  5590.8  108.29  5890.8  107.89
  5900.8  108.29  6440.8  108.49  6445.4  108.42  6466.5  108.09
BR U #Mann= 8
  3350.8     .08  4908.7     .04  4954.3    .015  4983.6     .04  5016.4    .015
    5043     .04  5100.6     .05    5322     .08
BR D #Sta/Elev= 108
  3349.1  111.21  3369.1  111.15  3409.1  111.36  3419.1  111.11  3439.1  110.43
  3449.1  110.34  3469.1  110.44  3489.1  110.65  3499.1  110.66  3539.1  110.23
  3549.1  110.32  3579.1  111.19  3589.1   111.2  3599.1  111.01  3639.1  110.79
  3659.1  110.94  3689.1  110.89  3729.1  110.34  3769.1  110.58  3799.1  110.41
  3809.1  110.46  3839.1  110.17  3869.1  110.07  3889.1  109.86  3939.1  110.04
  3959.1     110  4019.1  109.91  4039.1  109.89  4079.1  109.61  4109.1  109.51
  4149.1  109.52  4179.1   109.6  4219.1  109.51  4259.1  109.49  4279.1  109.58
  4319.1  109.39  4359.1  109.39  4379.1  109.45  4429.1  109.24  4469.1  109.32
  4549.1  109.28  4579.1  109.18  4629.1  109.23  4679.1     109  4719.1  107.96
  4749.1  107.95  4769.1  108.07  4795.7  109.05  4851.1  109.47  4908.7  110.61
  4942.9  111.78  4954.3   108.2    4972  102.14  4979.1  101.04  4983.6   99.87
  4985.5    99.3  4987.4   97.82  4999.3   97.82    5013   98.84  5013.6   98.67
  5014.5   99.25  5016.4  100.63    5023  101.74    5043   108.4  5057.6  111.58
  5100.6  110.15  5159.4  109.06  5219.1   108.5  5269.1  108.17  5299.1  108.34
  5319.1  108.12  5369.1  107.82  5399.1   108.2  5409.1   108.3  5469.1  108.33
  5489.1  108.41  5559.1  108.42  5569.1  108.39  5599.1  108.26  5639.1  108.73
  5669.1  108.56  5699.1  108.74  5719.1  108.67  5739.1  108.69  5769.1   108.3
  5789.1  108.37  5819.1  108.12  5839.1  108.26  5869.1  108.28  5899.1   108.3
  5939.1  108.33  5959.1   108.4  5979.1  108.41  6009.1  108.05  6039.1  107.75
  6089.1  107.65  6109.1  107.86  6139.1  107.95  6189.1  107.87  6199.1  107.67
  6249.1  107.47  6299.1  107.51  6339.1  107.45  6359.1  107.36  6409.1  107.43
  6440.8  108.49  6445.4  108.42  6466.5  108.09
BR D #Mann= 8
  3349.1     .08  4908.7     .04  4954.3    .015  4983.6     .04  5016.4    .015
    5043     .04  5100.6     .05  5319.1     .08
BC Design=,, 0 ,, 0 ,,,,,,

Type RM Length L Ch R = 1 ,6863.3  ,33.5,31.3,30.8
BEGIN DESCRIPTION:
US 290 - 2
E127-00-00-03
END DESCRIPTION:
XS GIS Cut Line= 2
      3050538.35     13887396.43      3053015.07     13885506.09
#Sta/Elev= 30
  3350.8  111.49  3410.8  111.89  3440.8  110.59  3450.8  111.29  3910.8  109.99
  3970.8  110.89  4080.8  109.59  4120.8  110.19  4190.8  109.39  4320.8  109.89
  4750.8  108.79  4926.4   111.5  4942.9  111.19    4972  102.14  4985.5    99.3
  4987.4   97.82  5013.6   98.67  5016.4  100.63    5023  101.74    5043   108.4
  5057.6  111.58  5086.7   111.2  5159.4  109.65  5170.8  108.19    5322  108.04
  5570.8  108.29  5580.8  108.99  5590.8  108.29  5890.8  107.89  6466.5  108.09
#Mann= 4 ,-1 , 0
  3350.8     .08       0  4926.4     .04       0  5086.7     .05       0
    5322     .08       0
#XS Ineff= 2 , 0
       0  4953.9   110.9  5044.5       0   110.9
Permanent Ineff=
       F       F
Bank Sta=4942.9,5057.6
XS Rating Curve= 0
Exp/Cntr=.5,.3

Type RM Length L Ch R = 1 ,6832.0  ,529.8,507,489.6
BEGIN DESCRIPTION:
US 290 - 1
Formerly Cross Section XS06.5
END DESCRIPTION:
XS GIS Cut Line= 2
      3050564.66     13887399.53      3052231.95     13886151.04
#Sta/Elev= 30
  3355.9   111.4  3405.9   111.2  3425.9   110.4  3795.9   110.6  4245.9   109.1
  4565.9   108.7  4645.9   109.3  4675.9   108.5  4695.9   107.5  4955.9   108.1
  4964.3  107.34  4970.5  106.19  4979.9  103.43  4988.4   99.99  4992.7   99.56
    4994   98.79  4997.8   98.14    5002   98.56  5006.5   98.52  5007.1   99.64
  5009.8  100.21  5018.9  104.14  5029.5  107.26  5035.9     106  5055.9   108.1
  5059.5  108.09  5285.9   108.3  5291.8   108.1  5315.9   107.3  5438.8   108.5
#Mann= 6 ,-1 , 0
  3355.9     .08       0  4964.3     .04       0  4970.5     .04       0
  5029.5     .04       0  5059.5     .05       0  5291.8     .08       0
Bank Sta=4970.5,5029.5
XS Rating Curve= 0
Exp/Cntr=.3,.1

Type RM Length L Ch R = 1 ,6325.0  ,857.3,838,822.7
BEGIN DESCRIPTION:
Cross Section XS06
***The Levee option was used on this cross-section does not describe a certified levee system but because after reviewing the mapping it was determined that water under that elevation could not back up into the lower-lying areas in the left overbank.***
END DESCRIPTION:
XS GIS Cut Line= 3
       3052228.1     13888002.26      3052283.94     13886916.41
       3052413.7     13886192.52
#Sta/Elev= 30
  3574.3   111.9  3594.3   110.4  3624.3   106.8  3654.3     107  3674.3   108.5
  3817.7  108.35  3964.3   108.9  4014.3   107.2  4044.3   107.3  4074.3   108.9
  4314.3   107.2  4394.3   108.8  4594.3   109.2  4623.7  107.52  4644.3   105.6
  4652.8   105.7  4681.6   105.8  4731.6     108  4831.6     108  4961.6  105.25
    4980  102.49  4988.5   99.05  4997.9    97.2  5006.6   97.58  5007.2    98.7
  5009.9   99.27    5019   103.2  5029.6  107.32  5045.2  107.12    5397   107.8
#Mann= 8 ,-1 , 0
  3574.3    .045       0  3817.7     .08       0  4623.7     .05       0
  4652.8      .1       0  4961.6     .04       0    4980     .04       0
    5019     .04       0  5045.2     .08       0
#XS Ineff= 2 , 0
       0 4961.34  106.93               0
Permanent Ineff=
       F       F
Bank Sta=4980,5019
XS Rating Curve= 0
Exp/Cntr=.3,.1

Type RM Length L Ch R = 1 ,5487.0  ,432,434,427.7
BEGIN DESCRIPTION:
Cross Section XS05
Located At: US RIOGRANDE
***Ineffective area in the right and left overbanks indicates ponding water***
***500yr possibly spills to and from E135-00-00 through small drainage channel that runs through the golf course.***
END DESCRIPTION:
XS GIS Cut Line= 3
      3053205.48     13888639.36      3053238.39     13886883.57
      3053045.84     13886149.06
#Sta/Elev= 30
    2986   110.8    3016   110.7    3086   107.1    3256   106.4    3356   103.7
    3646   105.8    3946   104.4    4306   103.9    4396   105.4    4526   103.8
  4615.9  105.61    4736   105.7  4782.1   103.6  4794.2  103.54  4842.1     105
  4969.5   105.2  4973.8  105.19  4994.1   96.99  5000.6   95.66  5003.7   95.63
  5005.9   96.94  5011.8   97.65    5023  100.74  5032.2  104.89  5052.7  104.73
  5202.1   106.5  5264.8  105.82  5312.1   105.3  5342.1   106.3  5501.4     107
#Mann= 8 ,-1 , 0
    2986    .045       0  4615.9     .08       0  4794.2    .045       0
  4969.5     .04       0  4973.8     .04       0  5032.2     .04       0
  5052.7     .05       0  5264.8      .1       0
#XS Ineff= 3 ,-1
 3083.46 4704.53  107.14 4704.53 4923.48  106.03 5067.69  5501.4  105.97
Permanent Ineff=
       F       F       F
Bank Sta=4973.8,5032.2
XS Rating Curve= 0
Exp/Cntr=.3,.1