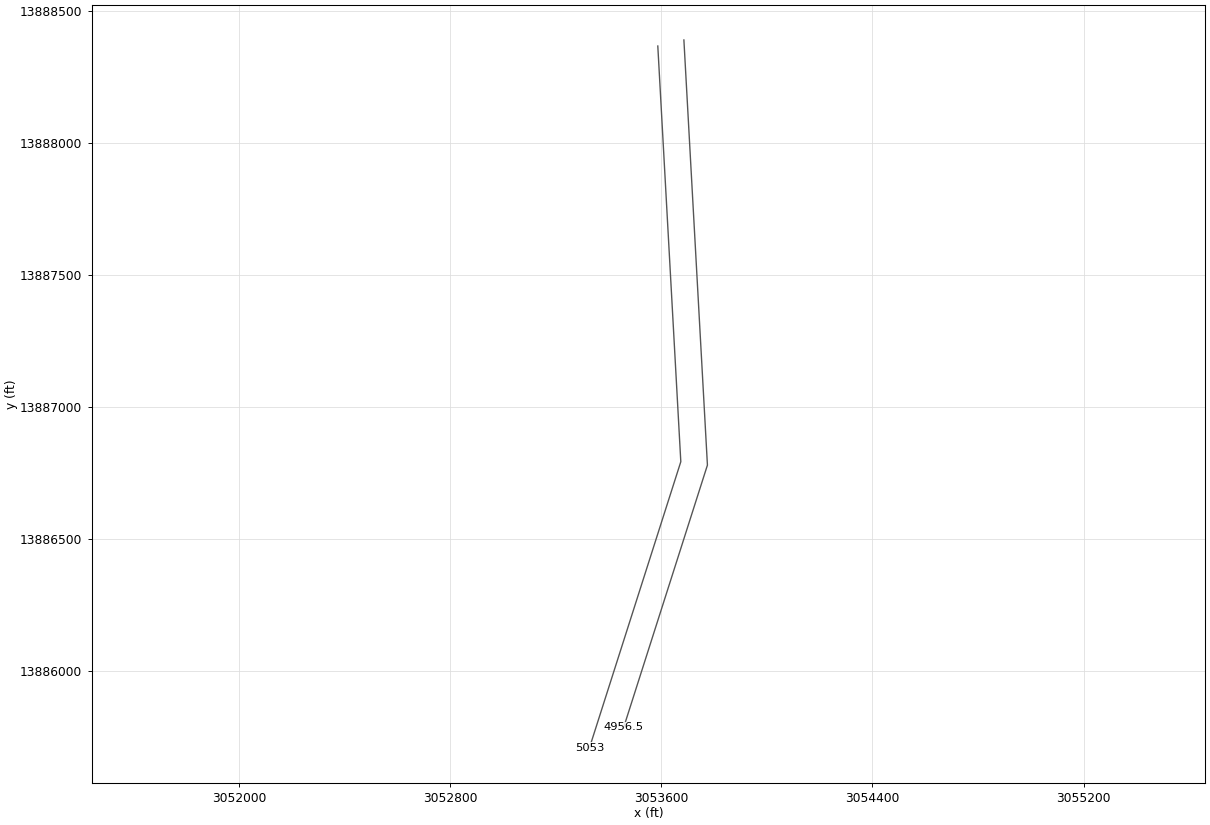
HEC-RAS study E127-00-00.prj: E127-00-00

--- E127-00-00.g01 (geometry) --- (continued)

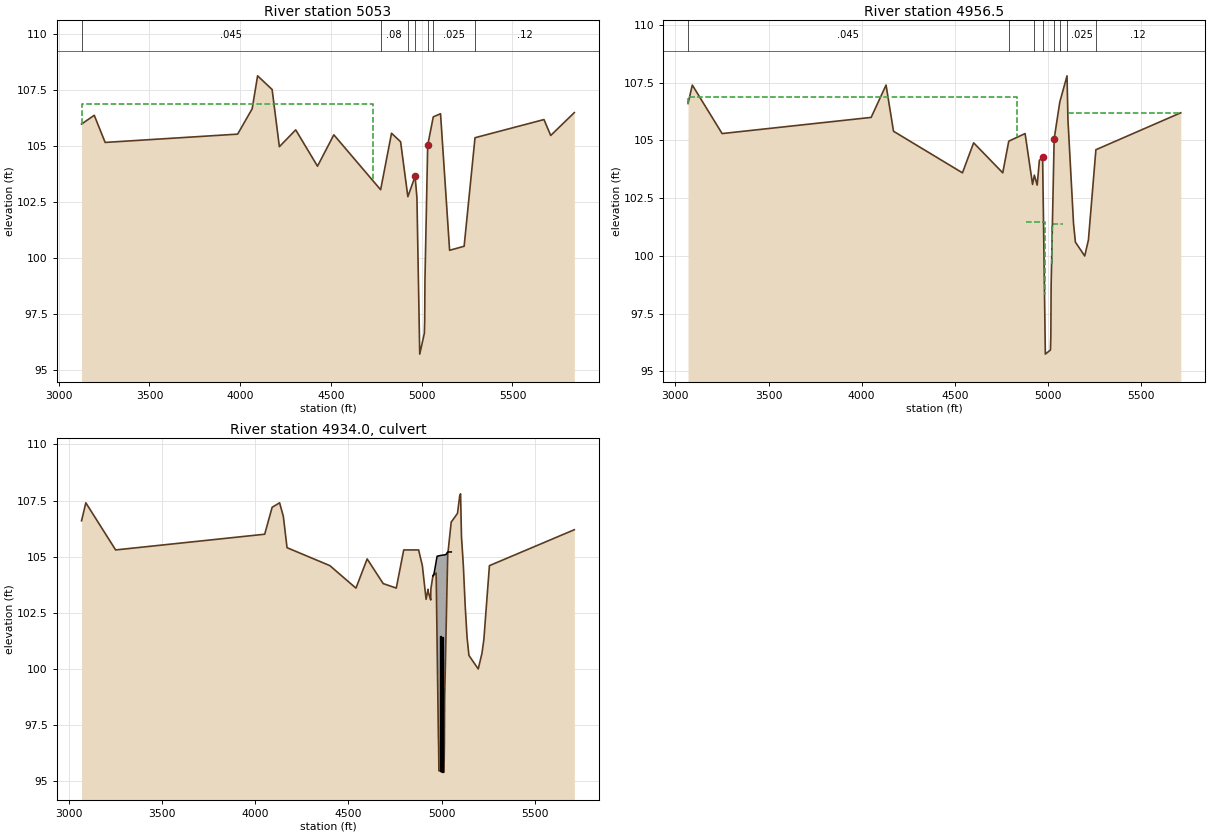
Type RM Length L Ch R = 1 ,5053    ,100.1,96.5,96
BEGIN DESCRIPTION:
TP#16300 - 4
Interpolated channel, LIDAR overbank
***Blocked obstruction for offline dention pond in right overbank***
END DESCRIPTION:
XS GIS Cut Line= 3
      3053586.72      13888366.9      3053673.92     13886791.51
        3053328.      13885708.2
#Sta/Elev= 30
  3125.8  105.99  3195.8  106.38  3255.8  105.17  3985.8  105.54  4065.8  106.67
  4095.8  108.14  4175.8  107.53  4215.8  104.98  4305.8  105.73  4425.8  104.11
  4515.8  105.51  4773.7  103.06  4833.7  105.58  4883.7   105.2  4923.7  102.75
  4963.7  103.66  4973.7   102.7 4989.14   95.73 5014.56   96.66 5016.41   97.21
  5017.9   99.05 5033.02  105.04  5063.7  106.31  5103.7  106.45  5153.7  100.36
  5233.7  100.54  5293.7  105.38  5673.7  106.19  5710.8  105.48  5840.8   106.5
#Mann= 7 ,-1 , 0
  3125.8    .045       0  4773.7     .08       0  4923.7     .04       0
  4963.7     .04       0 5033.02     .04       0  5063.7    .025       0
  5293.7     .12       0
#XS Ineff= 2 ,-1
  3125.8  4733.2  106.88 5105.09  5840.8   106.2
Permanent Ineff=
       T       F
#Block Obstruct= 2 , 0
       0                    5080       0     105
Bank Sta=4963.7,5033.02
XS Rating Curve= 0
Exp/Cntr=.5,.3

Type RM Length L Ch R = 1 ,4956.5  ,46.7,45,44.8
BEGIN DESCRIPTION:
TP#16300 - 3
E127-00-00-02a
***Blocked obstruction for offline dention pond in right overbank***
***Ineffective area in the right and left overbanks indicates ponding water***
***500yr possibly spills to and from E135-00-00 through small drainage channel that runs through the golf course.***
END DESCRIPTION:
XS GIS Cut Line= 5
 3053685.600056913888389.8412091      3053686.56      13888372.5
      3053774.79     13886778.64      3053462.81     13885801.68
  3053457.52667213885785.1353493
#Sta/Elev= 30
  3067.9   106.6  3090.9   107.4  3250.9   105.3  4050.9     106  4130.9   107.4
  4170.9   105.4  4540.9   103.6  4600.9   104.9  4757.2   103.6  4789.5  104.97
  4877.2   105.3  4917.2   103.1  4926.8   103.5  4942.1  103.07  4953.8  104.14
  4971.2  104.27  4985.9   95.75  5013.3   95.93  5015.3   96.52  5016.9   98.71
  5033.2  105.07  5063.6  106.67  5102.3   107.8  5107.2   105.9  5137.2   101.4
  5147.2   100.6  5197.2     100    5217  100.69  5257.2   104.6  5712.8   106.2
#Mann= 8 ,-1 , 0
  3067.9    .045       0  4789.5     .08       0  4926.8     .04       0
  4971.2     .04       0  5033.2     .04       0  5063.6     .12       0
  5102.3    .025       0  5257.2     .12       0
#XS Ineff= 4 ,-1
  3067.9  4833.2  106.88    4880 4981.47  101.46 5019.33    5080   101.4
 5105.09 5712.79   106.2
Permanent Ineff=
       T       F       F       F
#Block Obstruct= 2 , 0
       0                    5080       0     105
Bank Sta=4971.2,5033.2
XS Rating Curve= 0
Exp/Cntr=.5,.3

Type RM Length L Ch R = 2 ,4934.0  ,,,
BEGIN DESCRIPTION:
TP#16300
Structure ID: E127-00-00-02a
END DESCRIPTION:
Bridge Culvert--1,0,-1,-1, 0
Deck Dist Width WeirC Skew NumUp NumDn MinLoCord MaxHiCord MaxSubmerge Is_Ogee
10,25,2.6,0, 16, 16, , , .95, 0, ,,,
  4953.8  4960.2  4971.2  4976.2  4983.1  4984.6  4985.9  4999.3  4999.6  5013.3
  5015.3  5016.9  5023.2  5033.2    5052  5052.6
  104.14  104.26  104.78  105.02  105.03  105.03  105.04  105.06  105.06  105.08
  105.08  105.08  105.09  105.21  105.21  105.21
                                                                                
                                                
  4953.8  4960.2  4971.2  4976.2  4983.1  4984.6  4985.9  4999.3  4999.6  5013.3
  5015.3  5016.9  5023.2  5033.2    5052  5052.6
  104.14  104.26  104.78  105.02  105.03  105.03  105.04  105.06  105.06  105.08
  105.08  105.08  105.09  105.21  105.21  105.21
                                                                                
                                                
BR Coef= 1 , 1 , 0 ,1.25, 0 ,,,.8,0,2,0,
WSPro=,,,, 1 ,,,, 0 ,,,, 0 ,,,,-1 ,-1 ,-1 , 0 , 0 , 0 , 0 , 0
Culvert=2,6,8,25,.015,.4,1,8,1,95.46,4995.4,95.38,4995.4,Culvert #1  , 0 ,10
Culvert Bottom n=.015
Culvert=2,6,8,25,.018,.4,1,8,1,95.4,5005.4,95.38,5005.4,Culvert #2  , 0 ,10
Culvert Bottom n=.018
BR U #Sta/Elev= 75
  3067.9   106.6  3090.9   107.4  3237.9  105.47  3250.9   105.3  4050.9     106
  4067.9  106.51  4090.9   107.2  4130.9   107.4  4150.9   106.8  4170.9   105.4
  4377.9  104.68  4400.9   104.6  4457.9  104.19  4527.9  103.69  4540.9   103.6
  4600.9   104.9    4687   103.8  4687.2   103.8  4757.2   103.6  4789.5  104.97
  4797.2   105.3    4857   105.3  4877.2   105.3  4897.2   104.6  4917.2   103.1
  4926.8   103.5    4927  103.51    4928  103.55  4928.9  103.43  4941.3  103.09
  4941.9  103.08  4942.1  103.07  4942.7  103.55  4953.8  104.14  4960.2  104.19
  4971.2  104.27  4976.2  101.23  4983.1   97.03  4984.6   96.53  4985.9   95.46
  4999.3   95.46  4999.6    95.4  5013.3    95.4  5015.3   96.52  5016.9   98.71
  5023.2  101.17  5025.5  102.07  5033.2  105.07    5052  106.54  5052.6  106.55
  5063.6  106.67  5085.7  106.93  5086.5  106.98    5087  107.01    5097  107.66
  5097.6   107.7  5102.3   107.8  5107.2   105.9    5117  104.63  5117.2   104.6
  5127.2   102.8    5137  101.43  5137.2   101.4    5147  100.62  5147.2   100.6
    5167  100.36    5197     100  5197.2     100    5217  100.69  5217.2   100.7
  5227.2   101.3    5237  102.38    5247  103.48  5257.2   104.6  5712.8   106.2
BR U #Mann= 8
  3067.9    .045  4789.5     .08  4926.8     .04  4971.2     .04  5033.2     .04
  5063.6     .12  5102.3    .025  5257.2     .12
BR D #Sta/Elev= 75
  3067.9   106.6  3090.9   107.4  3237.9  105.47  3250.9   105.3  4050.9     106
  4067.9  106.51  4090.9   107.2  4130.9   107.4  4150.9   106.8  4170.9   105.4
  4377.9  104.68  4400.9   104.6  4457.9  104.19  4527.9  103.69  4540.9   103.6
  4600.9   104.9    4687   103.8  4687.2   103.8  4757.2   103.6  4789.5  104.97
  4797.2   105.3    4857   105.3  4877.2   105.3  4897.2   104.6  4917.2   103.1
  4926.8   103.5    4927  103.51    4928  103.55  4928.9  103.43  4941.3  103.09
  4941.9  103.08  4942.1  103.07  4942.7  103.55  4953.8  104.14  4960.2  104.19
  4971.2  104.27  4976.2  100.73  4983.1   96.53  4984.6   96.03  4985.9   95.25
  4999.3   95.28  4999.6   95.28  5013.3   95.43  5015.3   96.02  5016.9   98.21
  5023.2  100.67  5025.5  101.57  5033.2  105.07    5052  106.54  5052.6  106.55
  5063.6  106.67  5085.7  106.93  5086.5  106.98    5087  107.01    5097  107.66
  5097.6   107.7  5102.3   107.8  5107.2   105.9    5117  104.63  5117.2   104.6
  5127.2   102.8    5137  101.43  5137.2   101.4    5147  100.62  5147.2   100.6
    5167  100.36    5197     100  5197.2     100    5217  100.69  5217.2   100.7
  5227.2   101.3    5237  102.38    5247  103.48  5257.2   104.6  5712.8   106.2
BR D #Mann= 8
  3067.9    .045  4789.5     .08  4926.8     .04  4971.2     .04  5033.2     .04
  5063.6     .12    5117    .025  5257.2     .12
BC Design=,, 0 ,, 0 ,,,,,,