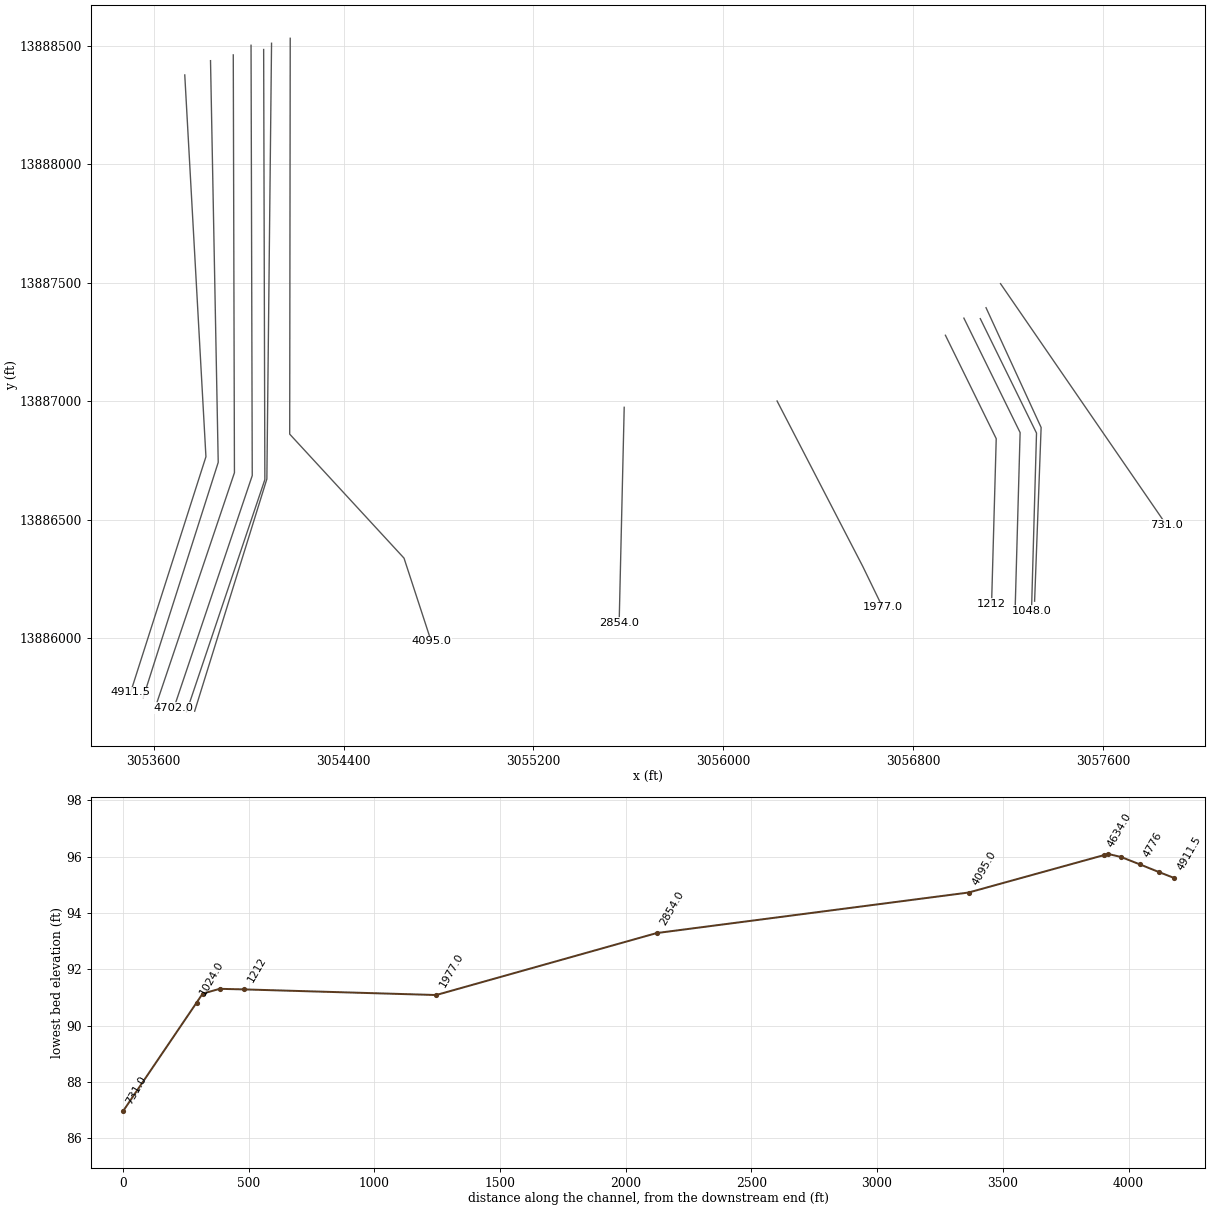
HEC-RAS study E127-00-00.prj: E127-00-00

--- E127-00-00.g01 (geometry) --- (continued)

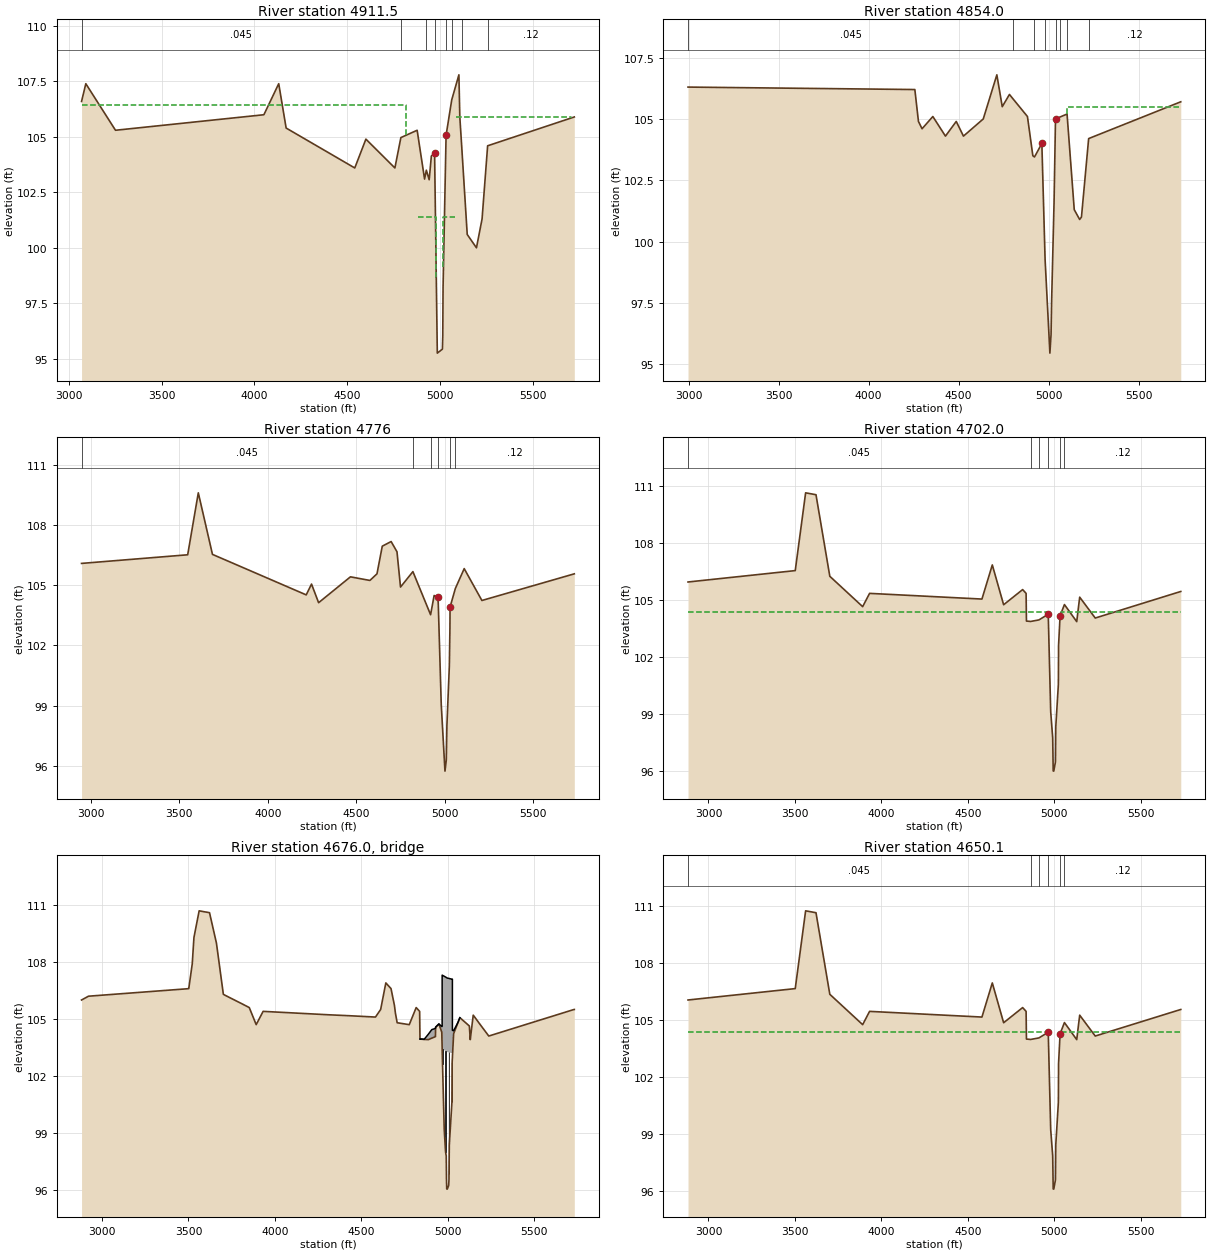
Type RM Length L Ch R = 1 ,4911.5  ,56.9,57.5,56.8
BEGIN DESCRIPTION:
TP#16300 - 2
E127-00-00-02a
***Blocked obstruction for offline dention pond in right overbank***
***Ineffective area in the right and left overbanks indicates ponding water***
***500yr possibly spills to and from E135-00-00 through small drainage channel that runs through the golf course.***
END DESCRIPTION:
XS GIS Cut Line= 5
 3053730.650786513888377.5549612      3053731.56     13888361.13
      3053819.84     13886766.35      3053507.58     13885788.52
 3053502.575792813885772.8495204
#Sta/Elev= 30
  3067.9   106.6  3090.9   107.4  3250.9   105.3  4050.9     106  4130.9   107.4
  4170.9   105.4  4540.9   103.6  4600.9   104.9  4757.2   103.6  4789.5  104.97
  4877.2   105.3  4917.2   103.1  4926.8   103.5  4942.1  103.07  4953.8  104.14
  4971.2  104.27  4985.9   95.25  5013.3   95.43  5015.3   96.02  5016.9   98.21
  5033.2  105.07  5063.6  106.67  5102.3   107.8  5107.2   105.9    5117  104.63
  5147.2   100.6    5197     100  5227.2   101.3  5257.2   104.6  5724.5   105.9
#Mann= 8 ,-1 , 0
  3067.9    .045       0  4789.5     .08       0  4926.8     .04       0
  4971.2     .04       0  5033.2     .04       0  5063.6     .12       0
    5117    .025       0  5257.2     .12       0
#XS Ineff= 4 ,-1
  3067.9 4818.67  106.42    4880 4980.36  101.38 5019.08 5079.77  101.38
 5085.59 5709.17  105.92
Permanent Ineff=
       T       F       F       F
#Block Obstruct= 2 , 0
       0                    5080       0     105
Bank Sta=4971.2,5033.2
XS Rating Curve= 0
Exp/Cntr=.5,.3

Type RM Length L Ch R = 1 ,4854.0  ,74.9,78,73.1
BEGIN DESCRIPTION:
TP#16300 - 1
Formerly Cross Section XS04.9
***Blocked obstruction for offline dention pond in right overbank***
***Ineffective area in the right and left overbanks indicates ponding water***
END DESCRIPTION:
XS GIS Cut Line= 3
      3053839.16     13888437.82      3053871.62     13886742.66
      3053555.52     13885750.02
#Sta/Elev= 30
  2996.5   106.3  4256.5   106.2  4276.5   104.9  4296.5   104.6  4356.5   105.1
  4426.5   104.3  4486.5   104.9  4526.5   104.3  4636.5     105    4712   106.8
    4742   105.5    4782     106  4801.8  105.82    4882   105.1    4912   103.5
  4921.1  103.45    4962     104    4980   99.27  5006.7   95.45  5013.1   96.21
    5016   97.49  5029.8   101.6  5037.8     105    5063  105.08    5102   105.2
    5142   101.3    5172   100.9    5182     101    5222   104.2  5733.7   105.7
#Mann= 8 ,-1 , 0
  2996.5    .045       0  4801.8     .08       0  4921.1     .04       0
    4980     .04       0  5037.8     .04       0    5063     .12       0
    5102    .025       0    5222     .12       0
#XS Ineff= 2 , 0
         4700.87  105.92 5101.91          105.48
Permanent Ineff=
       F       F
#Block Obstruct= 2 , 0
       0                    5078       0     105
Bank Sta=4962,5037.8
XS Rating Curve= 0
Exp/Cntr=.3,.1

Type RM Length L Ch R = 1 ,4776    ,75.4,74,73.9
BEGIN DESCRIPTION:
Rio Grande - 4
Interpolated channel, LIDAR overbaks
END DESCRIPTION:
XS GIS Cut Line= 3
      3053935.04      13888462.1      3053939.96     13886699.12
       3053613.7     13885730.19
#Sta/Elev= 30
  2947.5  106.09  3547.5  106.52  3607.5  109.61  3687.5  106.54  4217.5  104.52
  4247.5  105.06  4287.5  104.13  4467.5  105.42  4577.5  105.24  4617.5  105.57
  4647.5  106.95  4697.5  107.18  4730.6  106.67  4750.6  104.91  4820.6  105.68
  4920.6  103.53  4940.6  104.49  4960.6  104.39  4963.8  104.13  4980.8   99.06
 5001.88   95.73 5009.27   96.27 5012.79      98 5026.66  100.99 5029.89  102.86
  5030.6  103.91  5060.6  104.84  5110.6  105.83  5210.6  104.24    5733  105.57
#Mann= 6 ,-1 , 0
  2947.5    .045       0  4820.6     .08       0  4920.6     .04       0
  4960.6     .04       0  5030.6     .04       0  5060.6     .12       0
#XS Ineff= 2 , 0
        4832.672105.12495068.869        104.9106
Permanent Ineff=
       F       F
Bank Sta=4960.6,5030.6
XS Rating Curve= 0
Exp/Cntr=.5,.3

Type RM Length L Ch R = 1 ,4702.0  ,55.9,51.9,51.5
BEGIN DESCRIPTION:
Rio Grande - 3
E127-00-00-02
END DESCRIPTION:
XS GIS Cut Line= 4
 3054009.927509413888502.7482355      3054010.04      13888462.4
      3054014.99     13886686.93      3053684.77     13885706.26
#Sta/Elev= 30
  2881.6  105.96  3501.9  106.56  3561.9  110.66  3621.9  110.56  3701.9  106.26
  3891.9  104.66  3931.9  105.36  4581.9  105.06  4641.9  106.86  4707.4  104.76
  4817.4  105.56  4837.4  105.36  4839.4   103.9  4863.9  103.88  4911.4  103.96
  4965.5  104.26  4979.7   99.13  4991.3   97.74  4994.2      96  4997.3   95.99
  5007.2   96.47  5009.1   98.33  5024.1  100.56  5025.2  102.62  5034.1  104.18
  5059.2  104.77  5130.3  103.87  5147.4  105.16  5237.4  104.06  5732.2  105.46
#Mann= 6 ,-1 , 0
  2881.6    .045       0  4863.9     .08       0  4911.4     .04       0
  4965.5     .04       0  5034.1     .04       0  5059.2     .12       0
#XS Ineff= 2 , 0
       0  4957.8  104.37  5037.5       0  104.37
Permanent Ineff=
       F       F
Bank Sta=4965.5,5034.1
XS Rating Curve= 0
Exp/Cntr=.5,.3

Type RM Length L Ch R = 3 ,4676.0  ,,,
BEGIN DESCRIPTION:
RIO GRANDE STREET
Structure ID: E127-00-00-02
END DESCRIPTION:
Bridge Culvert--1,0,-1,-1, 0
Deck Dist Width WeirC Skew NumUp NumDn MinLoCord MaxHiCord MaxSubmerge Is_Ogee
10,31.9,2.6,0, 39, 39, , , .95, 0, ,,,
  4839.4  4839.9  4863.9  4888.1  4907.8  4911.4  4928.8  4929.9  4948.9  4965.5
  4967.3 4967.41  4967.5 4967.59  4967.7 4967.81  4969.9  4979.7  4987.5  4991.3
  4992.8  4994.2  4997.3    4999  5005.3  5007.2  5007.3  5009.1  5024.1  5025.2
 5026.79  5026.9 5027.01 5027.39  5027.5  5027.6  5034.1  5059.2  5070.1
  103.94  103.95  103.93   104.2  104.44  104.45   104.5  104.57  104.74   104.6
  104.61  104.61  104.61  104.61  107.31  107.31   107.3  107.25  107.21  107.19
  107.18  107.17  107.16  107.15  107.14  107.14  107.14  107.13   107.1   107.1
   107.1   107.1   104.4   104.4   104.4   104.4  104.38  104.82  105.07
  103.94  103.94  103.92  103.91  103.99     104  104.07  104.56  104.73   104.3
  103.61  103.57  103.54   103.5  103.46  103.42   103.4  103.35  103.31  103.29
  103.28  103.27  103.26  103.25  103.24  103.24  103.24  103.23   103.2   103.2
   103.2   103.2   103.2   103.2  103.06  103.08  104.22  104.81  105.07
  4839.4  4839.9  4863.9  4888.1  4907.8  4911.4  4928.8  4929.9  4948.9  4965.5
  4967.3 4967.41  4967.5 4967.59  4967.7 4967.81  4969.9  4979.7  4987.5  4991.3
  4992.8  4994.2  4997.3    4999  5005.3  5007.2  5007.3  5009.1  5024.1  5025.2
 5026.79  5026.9 5027.01 5027.39  5027.5  5027.6  5034.1  5059.2  5070.1
  103.94  103.95  103.93   104.2  104.44  104.45   104.5  104.57  104.74   104.6
  104.61  104.61  104.61  104.61  107.31  107.31   107.3  107.25  107.21  107.19
  107.18  107.17  107.16  107.15  107.14  107.14  107.14  107.13   107.1   107.1
   107.1   107.1   104.4   104.4   104.4   104.4  104.38  104.82  105.07
  103.94  103.94  103.92  103.91  103.99     104  104.07  104.56  104.73   104.3
  103.61  103.57  103.54   103.5  103.46  103.42   103.4  103.35  103.31  103.29
  103.28  103.27  103.26  103.25  103.24  103.24  103.24  103.23   103.2   103.2
   103.2   103.2   103.2   103.2  103.06  103.08  104.22  104.81  105.07
Pier Skew, UpSta & Num, DnSta & Num=  ,4969.9, 2 ,4969.9, 2 , 0 , 0 , 0 ,,
     1.1     1.1
  101.43  104.41
     1.1     1.1
  101.52   104.5
Pier Skew, UpSta & Num, DnSta & Num=  ,4987.5, 2 ,4987.5, 2 , 0 , 0 , 0 ,,
     1.5     1.5
   96.95  104.31
     1.5     1.5
   97.04   104.4
Pier Skew, UpSta & Num, DnSta & Num=  ,5007.4, 2 ,5007.4, 2 , 0 , 0 , 0 ,,
     1.5     1.5
   95.43  104.24
     1.5     1.5
   95.52  104.33
Pier Skew, UpSta & Num, DnSta & Num=  ,5024.1, 2 ,5024.1, 2 , 0 , 0 , 0 ,,
       1       1
   99.53   104.2
       1       1
   99.62  104.29
BR Coef= 1 , 1 , 1 ,1.25, 0 ,,,.8,0,1.2,0,
WSPro=,,,, 1 ,,,, 0 ,,,, 0 ,,,,-1 ,-1 ,-1 , 0 , 0 , 0 , 0 , 0
BR U #Sta/Elev= 82
  2881.6     106  2921.9   106.2  3491.6  106.59  3501.6   106.6  3501.9   106.6
  3521.9   107.9  3531.6  109.26  3531.9   109.3  3551.6  110.22  3561.9   110.7
  3591.6  110.65  3611.6  110.62  3621.9   110.6  3661.9     109  3701.9   106.3
  3711.6  106.25  3811.6  105.79  3851.9   105.6  3891.9   104.7  3931.9   105.4
  4311.6  105.22  4431.6  105.17  4581.9   105.1  4611.9   105.5  4641.9   106.9
  4671.9   106.6  4691.9   105.7  4697.4   105.3  4699.9  105.18  4707.4   104.8
  4777.4   104.7  4817.4   105.6  4837.4   105.4  4839.4  103.94  4839.9  103.94
  4863.9  103.92  4888.1  103.91  4907.8  103.99  4911.4     104  4928.8  104.07
  4929.9  104.56  4948.9  104.73  4965.5   104.3  4967.3  103.61 4967.41  103.57
  4967.5  103.54 4967.59   103.5  4967.7  103.46 4967.81  103.42  4969.9  102.62
  4979.7   99.17  4987.5   97.99  4991.3   97.78  4992.8   96.52  4994.2   96.04
  4997.3   96.03    4999   96.07  5005.3   96.22  5007.2   96.51  5007.3   96.73
  5009.1   98.37  5024.1   100.6  5025.2  102.66 5026.79  102.94  5026.9  102.96
 5027.01  102.98 5027.39  103.04  5027.5  103.06  5027.6  103.08  5034.1  104.22
  5059.2  104.81  5070.1  105.07  5078.8     105    5125  104.63  5129.9  103.96
  5130.3  103.91  5147.4   105.2  5159.9  105.05  5179.9   104.8  5237.4   104.1
  5730.6   105.5  5732.2   105.5
BR U #Mann= 6
  2881.6    .045  4863.9     .08  4911.4     .04  4965.5     .04  5034.1     .04
  5059.2     .12
BR U Banks=4965.5,5034.1
BR D #Sta/Elev= 82
  2881.6     106  2921.9   106.2  3491.6  106.59  3501.6   106.6  3501.9   106.6
  3521.9   107.9  3531.6  109.26  3531.9   109.3  3551.6  110.22  3561.9   110.7
  3591.6  110.65  3611.6  110.62  3621.9   110.6  3661.9     109  3701.9   106.3
  3711.6  106.25  3811.6  105.79  3851.9   105.6  3891.9   104.7  3931.9   105.4
  4311.6  105.22  4431.6  105.17  4581.9   105.1  4611.9   105.5  4641.9   106.9
  4671.9   106.6  4691.9   105.7  4697.4   105.3  4699.9  105.18  4707.4   104.8
  4777.4   104.7  4817.4   105.6  4837.4   105.4  4839.4  103.94  4839.9  103.94
  4863.9  103.92  4888.1  103.91  4907.8  103.99  4911.4     104  4928.8  104.07
  4929.9  104.56  4948.9  104.73  4965.5   104.3  4967.3   103.7 4967.41  103.66
  4967.5  103.63 4967.59  103.59  4967.7  103.55 4967.81  103.51  4969.9  102.71
  4979.7   99.26  4987.5   98.08  4991.3   97.87  4992.8   96.61  4994.2   96.13
  4997.3   96.12    4999   96.16  5005.3   96.31  5007.2    96.6  5007.3   96.82
  5009.1   98.46  5024.1  100.69  5025.2  102.75 5026.79  103.03  5026.9  103.05
 5027.01  103.07 5027.39  103.13  5027.5  103.15  5027.6  103.17  5034.1  104.31
  5059.2   104.9  5070.1  105.07  5078.8     105    5125  104.63  5129.9  103.96
  5130.3  103.91  5147.4   105.2  5159.9  105.05  5179.9   104.8  5237.4   104.1
  5730.6   105.5  5732.2   105.5
BR D #Mann= 6
  2881.6    .045  4863.9     .08  4911.4     .04  4965.5     .04  5034.1     .04
  5059.2     .12
BR D Banks=4965.5,5034.1
BC Design=,, 0 ,, 0 ,,,,,,

Type RM Length L Ch R = 1 ,4650.1  ,13.6,16.1,15.2
BEGIN DESCRIPTION:
Rio Grande - 2
E127-00-00-02
END DESCRIPTION:
XS GIS Cut Line= 4
 3054063.042190413888484.8971026      3054063.15     13888446.21
       3054068.1     13886669.92      3053737.62     13885688.45
#Sta/Elev= 30
  2881.6  106.07  3501.9  106.67  3561.9  110.77  3621.9  110.67  3701.9  106.37
  3891.9  104.77  3931.9  105.47  4581.9  105.17  4641.9  106.97  4707.4  104.87
  4817.4  105.67  4837.4  105.47  4839.4  104.01  4863.9  103.99  4911.4  104.07
  4965.5  104.37  4979.7   99.24  4991.3   97.85  4994.2   96.11  4997.3    96.1
  5007.2   96.58  5009.1   98.44  5024.1  100.67  5025.2  102.73  5034.1  104.29
  5059.2  104.88  5130.3  103.98  5147.4  105.27  5237.4  104.17  5732.2  105.57
#Mann= 6 ,-1 , 0
  2881.6    .045       0  4863.9     .08       0  4911.4     .04       0
  4965.5     .04       0  5034.1     .04       0  5059.2     .12       0
#XS Ineff= 2 , 0
       0  4957.8  104.37  5037.5       0  104.37
Permanent Ineff=
       F       F
Bank Sta=4965.5,5034.1
XS Rating Curve= 0
Exp/Cntr=.5,.3

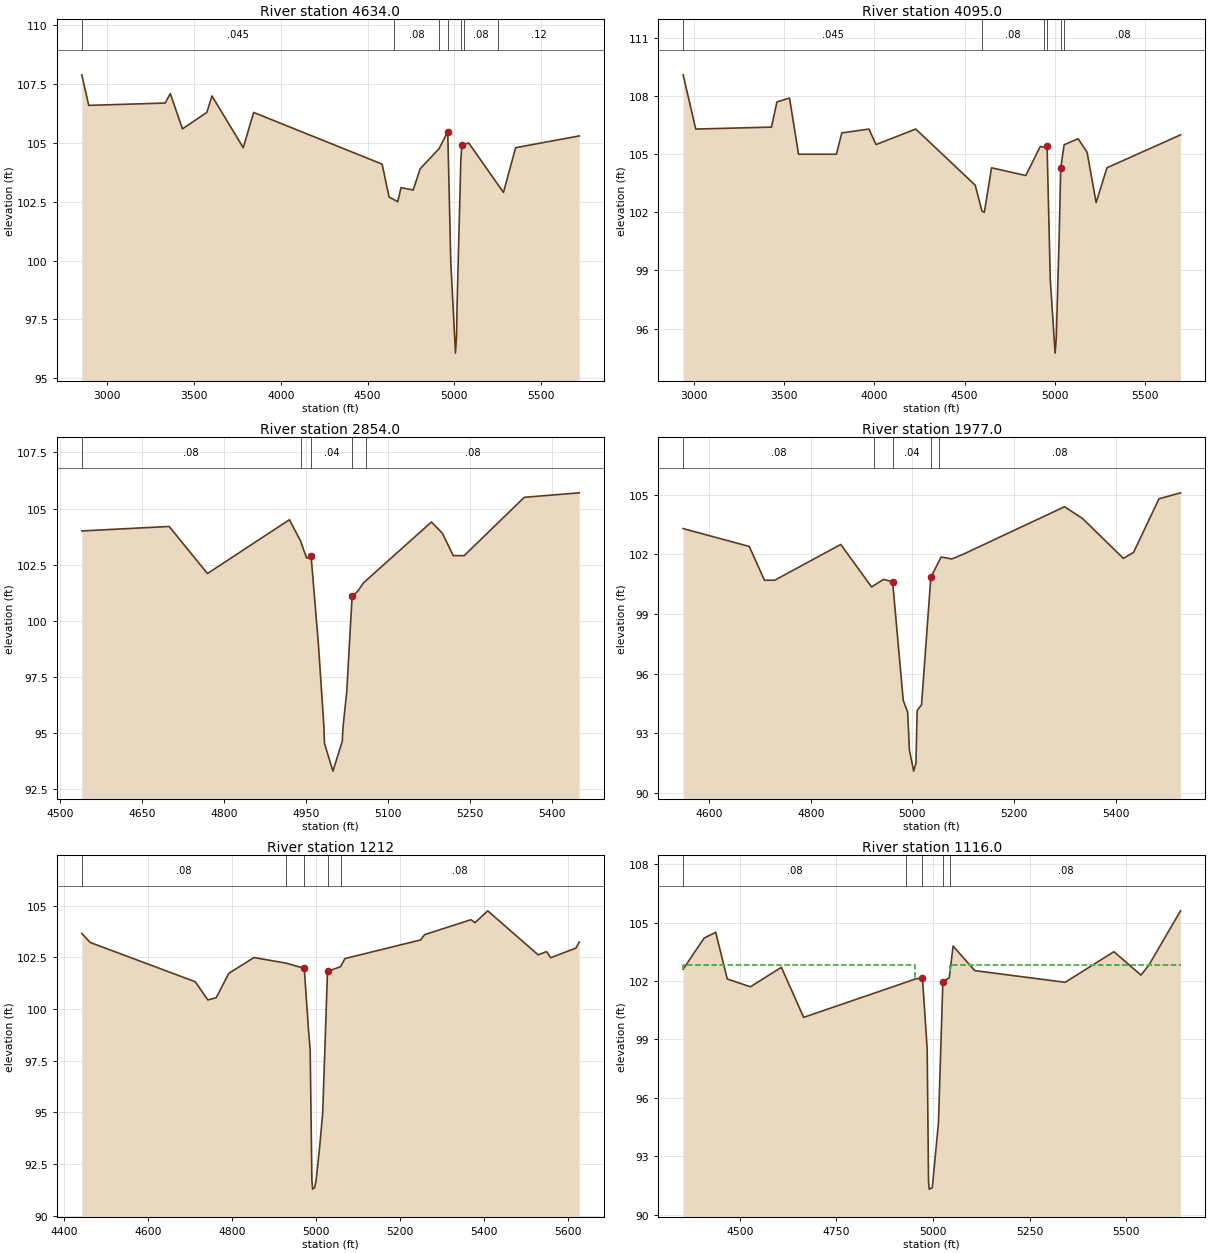
Type RM Length L Ch R = 1 ,4634.0  ,497.7,539,576.1
BEGIN DESCRIPTION:
Rio Grande - 1
Formerly Cross Section XS04.5
***Ineffective area in the right and left overbanks indicates ponding water***
END DESCRIPTION:
XS GIS Cut Line= 3
       3054096.3     13888511.29      3054076.58     13886672.46
      3053772.32     13885692.48
#Sta/Elev= 30
  2854.3   107.9  2894.3   106.6  3334.3   106.7  3364.3   107.1  3434.3   105.6
  3574.3   106.3  3604.3     107  3784.3   104.8  3844.3   106.3  4584.3   104.1
  4624.3   102.7    4653  102.59  4674.3   102.5  4693.2   103.1  4763.2     103
  4803.2   103.9  4912.3  104.76  4962.2  105.48    4980   99.88  5006.7   96.06
  5013.1   96.82    5016    98.1  5037.8  104.32  5043.2   104.9  5053.2  104.93
  5083.2     105  5251.4  103.23  5283.2   102.9  5353.2   104.8  5719.4   105.3
#Mann= 7 ,-1 , 0
  2854.3    .045       0    4653     .08       0  4912.3     .04       0
  4962.2     .04       0  5037.8     .04       0  5053.2     .08       0
  5251.4     .12       0
#XS Ineff= 2 , 0
         4896.51  104.38 5092.14          104.44
Permanent Ineff=
       F       F
Bank Sta=4962.2,5043.2
XS Rating Curve= 0
Exp/Cntr=.3,.1

Type RM Length L Ch R = 1 ,4095.0  ,1271.6,1241,1203.4
BEGIN DESCRIPTION:
Cross Section XS04
Located At: DS RIOGRANDE
***Ineffective area in the right and left overbanks indicates ponding water***
END DESCRIPTION:
XS GIS Cut Line= 4
      3054175.02     13888532.28      3054172.77     13886861.84
      3054654.49     13886338.43      3054769.21     13885986.93
#Sta/Elev= 30
  2939.1   109.1  3009.1   106.3  3429.1   106.4  3459.1   107.7  3529.1   107.9
  3579.1     105  3789.1     105  3819.1   106.1  3969.1   106.3  4009.1   105.5
  4229.1   106.3  4559.1   103.4  4596.4  102.06  4609.5     102  4649.5   104.3
  4839.5   103.9  4919.5   105.4  4941.8  105.36  4957.4  105.44  4975.2   98.55
  5001.9   94.73  5008.3   95.49    5025  100.88    5033  104.28  5052.1  105.49
  5129.5   105.8  5179.5   105.1  5229.5   102.5  5289.5   104.3  5697.6     106
#Mann= 6 ,-1 , 0
  2939.1    .045       0  4596.4     .08       0  4941.8     .04       0
  4957.4     .04       0    5033     .04       0  5052.1     .08       0
#XS Ineff= 2 , 0
         4648.91  104.03 5180.79          104.03
Permanent Ineff=
       F       F
Bank Sta=4957.4,5033
XS Rating Curve= 0
Exp/Cntr=.3,.1

Type RM Length L Ch R = 1 ,2854.0  ,849.9,877,896.1
BEGIN DESCRIPTION:
Cross Section XS03
***Ineffective area in the left overbank indicates ponding water***
END DESCRIPTION:
XS GIS Cut Line= 2
      3055582.21     13886975.01      3055560.92     13886064.74
#Sta/Elev= 25
  4539.3     104  4699.3   104.2  4769.3   102.1  4919.3   104.5  4939.4  103.57
  4940.2  103.52  4950.8  102.79  4959.1  102.87  4972.7   98.86  4982.5   95.26
  4983.5   94.53    4999   93.29  5016.1   94.62  5017.5   95.26  5024.3   96.83
  5034.1  101.08  5044.7  101.32  5054.8  101.68  5059.7  101.79  5179.3   104.4
  5199.3   103.9  5219.3   102.9  5239.3   102.9  5349.3   105.5  5449.8   105.7
#Mann= 5 ,-1 , 0
  4539.3     .08       0  4940.2     .04       0  4959.1     .04       0
  5034.1     .04       0  5059.7     .08       0
#XS Ineff= 2 , 0
         4909.35  103.19
Permanent Ineff=
       F       F
Bank Sta=4959.1,5034.1
XS Rating Curve= 0
Exp/Cntr=.3,.1

Type RM Length L Ch R = 1 ,1977.0  ,782.8,765,740.9
BEGIN DESCRIPTION:
Cross Section XS02
Located At: US SENATE AVE;
***Ineffective area in the right and left overbanks indicates ponding water***
END DESCRIPTION:
XS GIS Cut Line= 3
      3056226.32     13887001.63      3056587.27     13886303.77
      3056671.23      13886130.6
#Sta/Elev= 27
  4549.1   103.3  4679.1   102.4  4709.1   100.7  4729.1   100.7  4859.1   102.5
  4919.7  100.36  4924.4  100.44  4943.1  100.74    4961  100.63  4981.9   94.65
  4990.6   94.06  4994.1   92.15  5002.4   91.09  5006.9   91.49  5009.3   94.14
  5017.9   94.43  5036.2  100.85  5052.9  101.69  5056.4  101.87  5077.5  101.77
  5099.1     102  5299.1   104.4  5334.8   103.8  5414.8   101.8  5434.8   102.1
  5484.8   104.8  5527.2   105.1
#Mann= 5 ,-1 , 0
  4549.1     .08       0  4924.4     .04       0    4961     .04       0
  5036.2     .04       0  5052.9     .08       0
#XS Ineff= 2 , 0
         4859.04  102.33 5299.21          104.32
Permanent Ineff=
       F       F
Bank Sta=4961,5036.2
XS Rating Curve= 0
Exp/Cntr=.3,.1

Type RM Length L Ch R = 1 ,1212    ,101.9,96,95.6
BEGIN DESCRIPTION:
Senate - 4
Interpolated channel, LIDAR overbanks
END DESCRIPTION:
XS GIS Cut Line= 3
      3056935.62       13887279.       3057149.7     13886842.61
       3057130.1     13886145.17
#Sta/Elev= 30
  4442.1  103.66  4462.1  103.22  4712.1  101.32  4742.1  100.44  4762.1  100.55
  4792.1  101.73  4852.1  102.49  4928.2  102.22 4971.57  101.97 4981.66      99
 4985.67   98.02 4989.71   91.71 4991.56   91.29 4996.26   91.37 4999.62   91.69
 5007.75   93.24 5015.43   94.96 5026.87  101.82  5058.2  102.05  5068.2  102.44
  5248.2  103.34  5258.2   103.6  5368.2  104.32  5378.2  104.18  5408.2  104.75
  5528.2  102.62  5548.2  102.78  5558.2  102.48  5618.2  102.95  5625.9  103.24
#Mann= 5 ,-1 , 0
  4442.1     .08       0  4928.2     .04       0 4971.57     .04       0
 5026.87     .04       0  5058.2     .08       0
#XS Ineff= 2 , 0
       0  4852.1  102.49               0
Permanent Ineff=
       F       F
Bank Sta=4971.57,5026.87
XS Rating Curve= 0
Exp/Cntr=.5,.3

Type RM Length L Ch R = 1 ,1116.0  ,70.9,68,67.5
BEGIN DESCRIPTION:
Senate - 3
E127-00-00-01
END DESCRIPTION:
XS GIS Cut Line= 5
 3057013.442360613887351.2866804       3057025.4     13887326.91
      3057250.35     13886868.33      3057230.06      13886146.2
 3057229.297411613886119.0591425
#Sta/Elev= 25
  4353.4   102.6  4407.7   104.2  4437.7   104.5  4467.7   102.1  4527.7   101.7
  4607.7   102.7  4665.4  100.13  4931.5  101.94  4955.7  102.11  4972.9  102.14
  4985.1   98.51  4988.6   91.73  4990.2   91.31  4998.3   91.38  5014.2    94.7
  5025.7  101.94  5042.2  102.16  5044.8  102.58  5052.2  103.79  5108.4  102.53
  5342.2  101.93  5468.5   103.5  5538.5   102.3  5558.5   102.8  5640.9   105.6
#Mann= 5 ,-1 , 0
  4353.4     .08       0  4931.5     .04       0  4972.9     .04       0
  5025.7     .04       0  5044.8     .08       0
#XS Ineff= 2 , 0
       0 4954.48   102.8 5044.42       0   102.8
Permanent Ineff=
       F       F
Bank Sta=4972.9,5025.7
XS Rating Curve= 0
Exp/Cntr=.5,.3

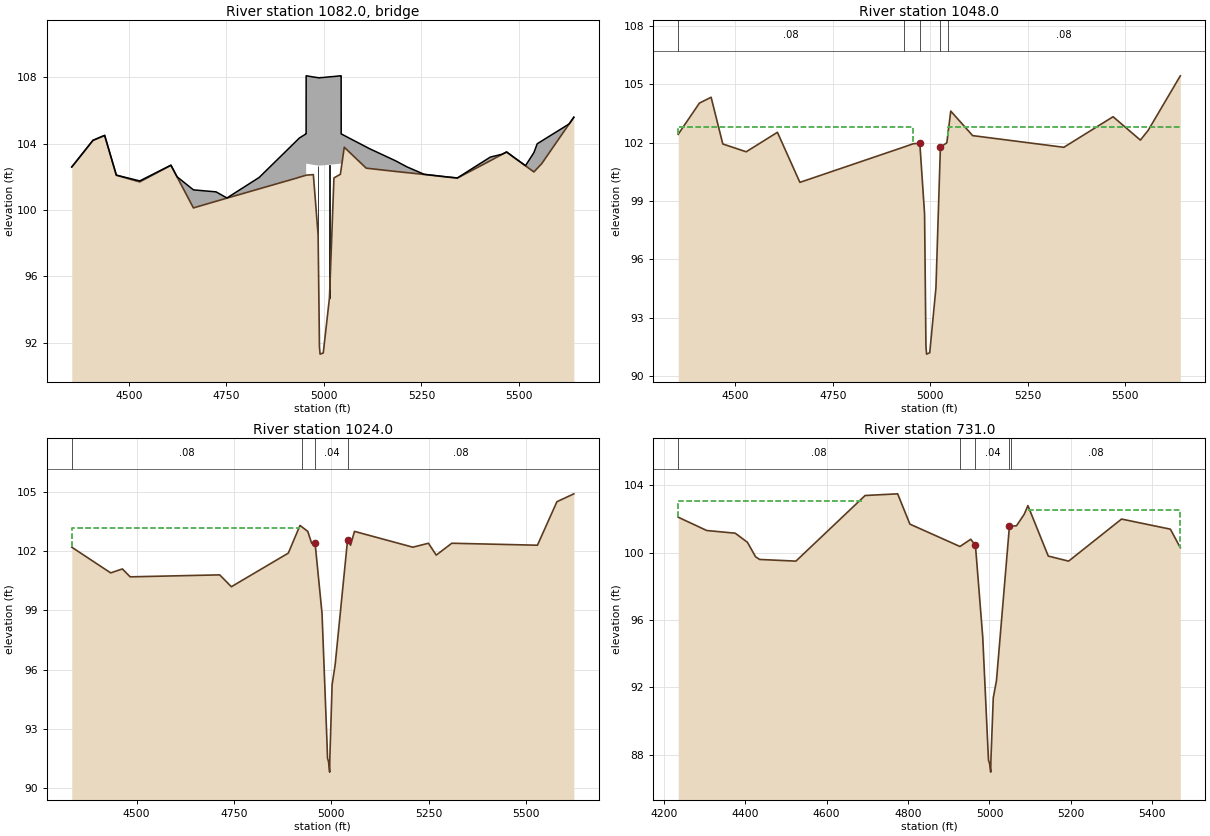
Type RM Length L Ch R = 3 ,1082.0  ,,,
BEGIN DESCRIPTION:
SENATE AVENUE
Structure ID: E127-00-00-01
END DESCRIPTION:
Bridge Culvert--1,0,-1,-1, 0
Deck Dist Width WeirC Skew NumUp NumDn MinLoCord MaxHiCord MaxSubmerge Is_Ogee
10,48,2.6,0, 57, 57, , , .95, 0, ,,,
  4353.4  4407.7  4437.7  4467.7  4527.7  4607.7  4623.4  4665.4  4723.4  4751.3
    4834  4931.5  4936.5  4954.1 4954.21 4954.29  4954.4 4954.48 4954.61  4955.7
  4972.9  4985.1  4986.5  4988.6  4990.2  4998.3  5014.2  5025.7  5042.2 5044.06
 5044.17 5044.28 5044.42  5044.5  5044.8  5052.2  5065.1  5108.4  5115.6    5184
  5212.7  5256.8  5316.9  5342.2  5426.9  5456.9  5466.9  5468.5  5486.9  5496.9
  5506.9  5516.9  5538.5  5546.9  5558.5    5629  5640.9
   102.6  104.21  104.51  102.11  101.76  102.71  102.01  101.22   101.1  100.73
  101.97  104.22  104.34   104.6   104.6   104.6   108.1   108.1   108.1   108.1
  108.03  107.99  107.98  107.98  107.99     108  108.04  108.06   108.1   108.1
   108.1   104.6   104.6   104.6  104.59   104.5  104.34  103.81  103.72  102.97
  102.61  102.16     102  101.94   103.2  103.37  103.49  103.51  103.19  103.02
  102.85  102.68  103.47     104  104.17   105.2   105.6
                                                                                
                                                           102.8   102.8   102.8
  102.73  102.69  102.68  102.68  102.69   102.7  102.74  102.76   102.8   102.8
   102.8   102.8   102.8
                                                                                
                                                        
  4353.4  4407.7  4437.7  4467.7  4527.7  4607.7  4623.4  4665.4  4723.4  4751.3
    4834  4931.5  4936.5  4954.1 4954.21 4954.29  4954.4 4954.48 4954.61  4955.7
  4972.9  4985.1  4986.5  4988.6  4990.2  4998.3  5014.2  5025.7  5042.2 5044.06
 5044.17 5044.28 5044.42  5044.5  5044.8  5052.2  5065.1  5108.4  5115.6    5184
  5212.7  5256.8  5316.9  5342.2  5426.9  5456.9  5466.9  5468.5  5486.9  5496.9
  5506.9  5516.9  5538.5  5546.9  5558.5    5629  5640.9
   102.6  104.21  104.51  102.11  101.76  102.71  102.01  101.22   101.1  100.73
  101.97  104.22  104.34   104.6   104.6   104.6   108.1   108.1   108.1   108.1
  108.03  107.99  107.98  107.98  107.99     108  108.04  108.06   108.1   108.1
   108.1   104.6   104.6   104.6  104.59   104.5  104.34  103.81  103.72  102.97
  102.61  102.16     102  101.94   103.2  103.37  103.49  103.51  103.19  103.02
  102.85  102.68  103.47     104  104.17   105.2   105.6
                                                                                
                                                           102.8   102.8   102.8
  102.73  102.69  102.68  102.68  102.69   102.7  102.74  102.76   102.8   102.8
   102.8   102.8   102.8
                                                                                
                                                        
Pier Skew, UpSta & Num, DnSta & Num=  ,4985.1, 2 ,4985.1, 2 , 0 , 0 , 0 ,,
     1.3     1.3
   96.25  103.69
     1.3     1.3
   96.21  103.65
Pier Skew, UpSta & Num, DnSta & Num=  ,5014.2, 2 ,5014.2, 2 , 0 , 0 , 0 ,,
     1.3     1.3
   93.56  103.74
     1.3     1.3
   93.52   103.7
BR Coef= 1 , 1 , 1 ,1.25, 0 ,,,.8,0,2,0,
WSPro=,,,, 1 ,,,, 0 ,,,, 0 ,,,,-1 ,-1 ,-1 , 0 , 0 , 0 , 0 , 0
BR U #Sta/Elev= 57
  4353.4   102.6  4407.7   104.2  4437.7   104.5  4467.7   102.1  4527.7   101.7
  4607.7   102.7  4623.4     102  4665.4  100.13  4723.4  100.53  4751.3  100.72
    4834  101.28  4931.5  101.94  4936.5  101.98  4954.1   102.1 4954.21   102.1
 4954.29   102.1  4954.4   102.1  4954.5   102.1 4954.61   102.1  4955.7  102.11
  4972.9  102.14  4985.1   98.51  4986.5    95.8  4988.6   91.73  4990.2   91.31
  4998.3   91.38  5014.2    94.7  5025.7  101.94  5042.2  102.16 5044.06  102.46
 5044.17  102.48 5044.28   102.5 5044.39  102.52  5044.5  102.53  5044.8  102.58
  5052.2  103.79  5065.1   103.5  5108.4  102.53  5115.6  102.51    5184  102.33
  5212.7  102.26  5256.8  102.15  5316.9  101.99  5342.2  101.93  5426.9  102.98
  5456.9  103.36  5466.9  103.48  5468.5   103.5  5486.9  103.18  5496.9  103.01
  5506.9  102.84  5516.9  102.67  5538.5   102.3  5546.9  102.51  5558.5   102.8
    5629   105.2  5640.9   105.6
BR U #Mann= 5
  4353.4     .08  4931.5     .04  4972.9    .015  5025.7     .04  5044.8     .08
BR U Banks=4972.9,5025.7
BR D #Sta/Elev= 57
  4353.4  102.56  4407.7  104.16  4437.7  104.46  4467.7  102.06  4527.7  101.66
  4607.7  102.66  4623.4  101.96  4665.4  100.09  4723.4  100.49  4751.3  100.68
    4834  101.24  4931.5   101.9  4936.5  101.94  4954.1  102.06 4954.21  102.06
 4954.29  102.06  4954.4  102.06  4954.5  102.06 4954.61  102.06  4955.7  102.07
  4972.9   102.1  4985.1   98.47  4986.5   95.76  4988.6   91.69  4990.2   91.27
  4998.3   91.34  5014.2   94.66  5025.7   101.9  5042.2  102.12 5044.06  102.42
 5044.17  102.44 5044.28  102.46 5044.39  102.48  5044.5  102.49  5044.8  102.54
  5052.2  103.75  5065.1  103.46  5108.4  102.49  5115.6  102.47    5184  102.29
  5212.7  102.22  5256.8  102.11  5316.9  101.95  5342.2  101.89  5426.9  102.94
  5456.9  103.32  5466.9  103.44  5468.5  103.46  5486.9  103.14  5496.9  102.97
  5506.9   102.8  5516.9  102.63  5538.5  102.26  5546.9  102.47  5558.5  102.76
    5629  105.16  5640.9  105.56
BR D #Mann= 5
  4353.4     .08  4931.5     .04  4972.9    .015  5025.7     .04  5044.8     .08
BR D Banks=4972.9,5025.7
BC Design=,, 0 ,, 0 ,,,,,,

Type RM Length L Ch R = 1 ,1048.0  ,18.6,24,17.5
BEGIN DESCRIPTION:
Senate - 2
E127-00-00-01
END DESCRIPTION:
XS GIS Cut Line= 5
 3057082.535967813887349.1279222      3057093.95     13887325.86
      3057319.45     13886866.17      3057299.11     13886142.81
 3057298.381541413886116.9035204
#Sta/Elev= 25
  4353.4  102.43  4407.7  104.03  4437.7  104.33  4467.7  101.93  4527.7  101.53
  4607.7  102.53  4665.4   99.96  4931.5  101.77  4955.7  101.94  4972.9  101.97
  4985.1   98.34  4988.6   91.56  4990.2   91.14  4998.3   91.21  5014.2   94.53
  5025.7  101.77  5042.2  101.99  5044.8  102.41  5052.2  103.62  5108.4  102.36
  5342.2  101.76  5468.5  103.33  5538.5  102.13  5558.5  102.63  5640.9  105.43
#Mann= 5 ,-1 , 0
  4353.4     .08       0  4931.5     .04       0  4972.9     .04       0
  5025.7     .04       0  5044.8     .08       0
#XS Ineff= 2 , 0
       0 4954.48   102.8 5044.42       0   102.8
Permanent Ineff=
       F       F
Bank Sta=4972.9,5025.7
XS Rating Curve= 0
Exp/Cntr=.5,.3

Type RM Length L Ch R = 1 ,1024.0  ,270.7,293,320.5
BEGIN DESCRIPTION:
Senate - 1
Formerly Cross Section xs01.5
***Ineffective area in the left overbank indicates ponding water***
END DESCRIPTION:
XS GIS Cut Line= 3
      3057106.78     13887395.27      3057338.87     13886889.84
      3057311.43     13886156.84
#Sta/Elev= 30
  4333.3   102.2  4433.3   100.9  4463.3   101.1  4483.3   100.7  4713.3   100.8
  4743.3   100.2  4889.5   101.9  4919.5   103.3  4923.6  103.24  4939.5     103
  4949.5   102.4 4958.25  102.42 4976.15   98.85 4989.25   92.15 4990.25   91.53
 4992.95   91.34 4995.75   90.82 4996.25   91.55 5002.05   95.24 5009.85   96.25
 5041.75  102.57  5049.5   102.3  5059.5     103  5209.5   102.2  5249.5   102.4
  5269.5   101.8  5309.5   102.4  5529.5   102.3  5579.5   104.5    5623   104.9
#Mann= 4 ,-1 , 0
  4333.3     .08       0  4923.6     .04       0 4958.25     .04       0
 5041.75     .08       0
#XS Ineff= 2 , 0
         4919.65  103.17
Permanent Ineff=
       F       F
Bank Sta=4958.25,5041.75
XS Rating Curve= 0
Exp/Cntr=.3,.1

Type RM Length L Ch R = 1 ,731.0   ,0,0,0
BEGIN DESCRIPTION:
Cross Section xs01
***Ineffective area in the right and left overbanks indicates ponding water***
END DESCRIPTION:
XS GIS Cut Line= 2
      3057167.72      13887496.8      3057865.87     13886479.95
#Sta/Elev= 30
  4235.3  102.11  4305.3  101.32  4375.3  101.16  4405.3  100.62  4425.3   99.76
  4435.3    99.6  4524.4    99.5  4694.4   103.4  4774.4   103.5  4804.4   101.7
  4927.4  100.37    4954   100.8  4965.5  100.43  4983.4   94.99  4997.5   87.67
  5000.2   87.48    5003   86.96  5003.5   87.69  5009.3   91.38  5017.1   92.39
    5049  101.58  5052.5  101.58  5066.3   101.6  5085.4  102.29  5094.4   102.8
  5144.4    99.8  5194.4    99.5  5324.4     102  5444.4   101.4  5468.8   100.3
#Mann= 5 ,-1 , 0
  4235.3     .08       0  4927.4     .04       0  4965.5     .04       0
    5049     .04       0  5052.5     .08       0
#XS Ineff= 2 , 0
         4691.35  103.05 5094.85          102.54
Permanent Ineff=
       F       F
Bank Sta=4965.5,5049
XS Rating Curve= 0
Exp/Cntr=.3,.1

Chan Stop Cuts=-1